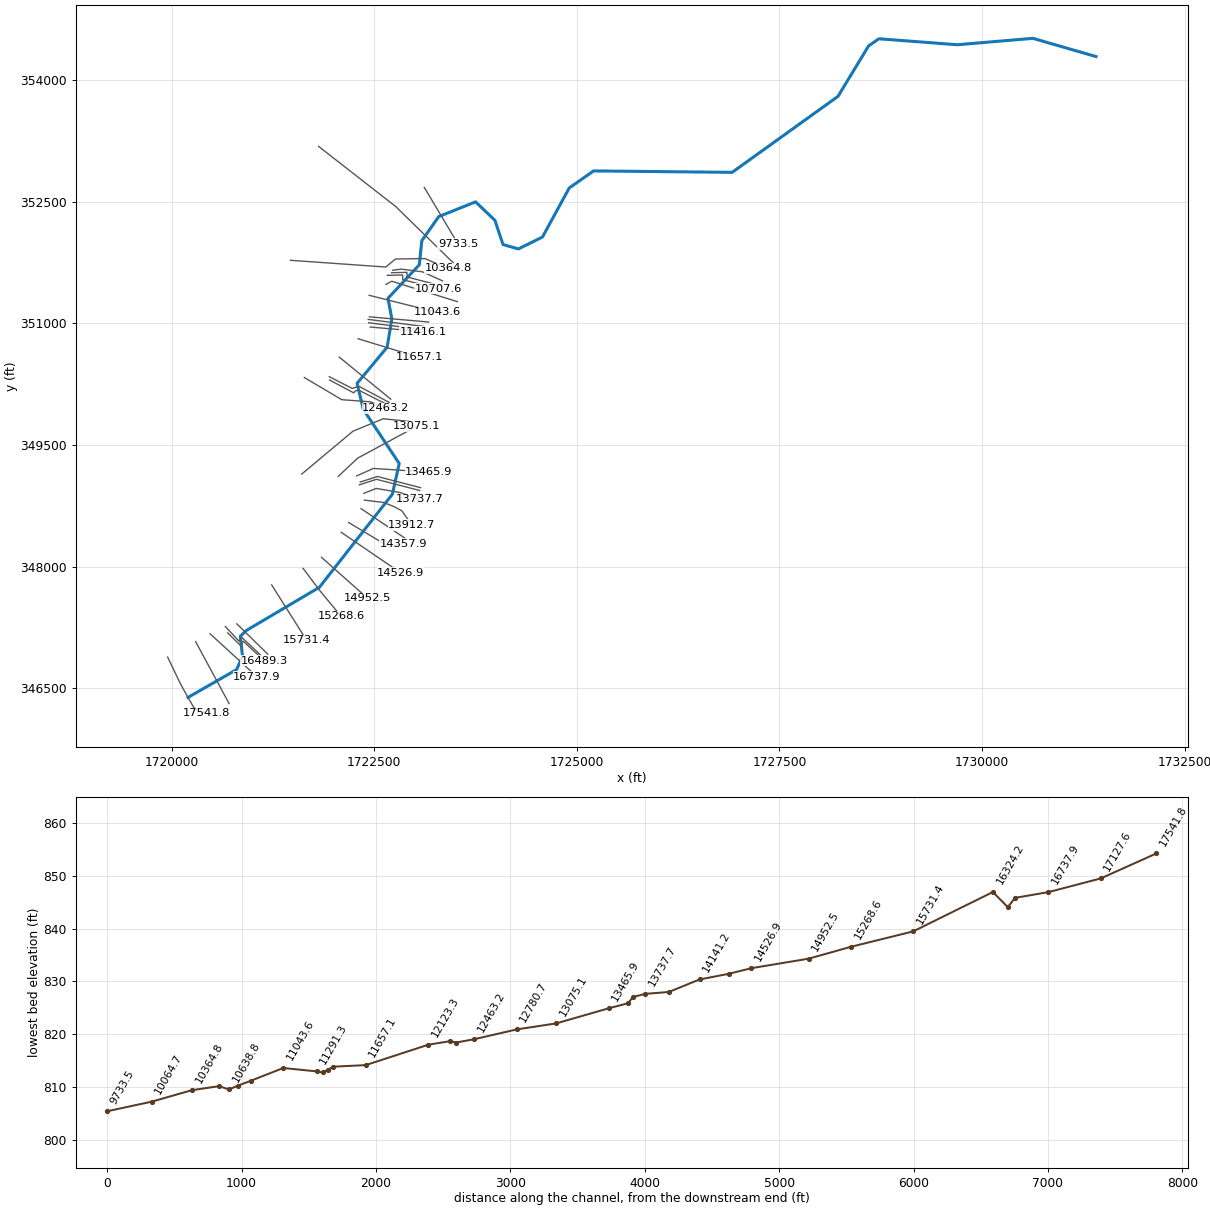
--- HEWETTCK.prj (project) ---

Proj Title=HEWETTCK
Current Plan=p01
Default Exp/Contr=0,0
English Units
Geom File=g01
Flow File=f01
Plan File=p01
BEGIN DESCRIPTION:
END DESCRIPTION:
DSS Export Rating Curves= 0
DSS Export Rating Curve Sorted= 0
DSS Export Volume Flow Curves= 0
DXF OffsetX= 0
DXF OffsetY= 0
DXF ScaleX= 0
DXF ScaleY= 0

--- HEWETTCK.p01 (plan) ---

Plan Title=Floodplain
Program Version=4.00
Geom File=g01
Flow File=f01
K Sum by GR=0
Std Step Tol=0.01
Critical Tol=0.01
Num of Std Step Trials=20
Max Error Tol=0.3
Flow Tol Ratio=0.001
Split Flow NTrial=30
Split Flow Tol=0.02
Split Flow Ratio=0.02
Log Output Level=0
Friction Slope Method=1
Unsteady Friction Slope Method=2
Unsteady Bridges Friction Slope Method=1
Global Log Level=0
CheckData=False
Run HTab=0
Run UNet=0
Run PostProcess=0
UNET Theta=0
UNET Theta Warmup=0
UNET ZTol=0
UNET ZSATol=0
UNET MxIter=0
UNET MaxInSteps=0
UNET DtIC=0
UNET DtMin=0
UNET MaxCRTS=0
UNET WFStab=0
UNET SFStab=0
UNET WFX=0
UNET SFX=0
UNET DSS MLevel=0
UNET DZMax Abort=0
UNET Convert EG Bridges=0
UNET Use Existing IB Tables=0
UNET Froude Limit=0
UNET Froude Power=0
Write IC File=0
Echo Input=False
Echo Output=False
Write Detailed=0

--- HEWETTCK.f01 (steady flow) ---

Flow Title=NFF Regression Equation
Program Version=4.00
Number of Profiles=1
Profile Names=P100yr
River Rch & RM=HEWETTCK,Main      ,17541.8
2652.393
River Rch & RM=HEWETTCK,Main      ,14952.5
2705.312
River Rch & RM=HEWETTCK,Main      ,12780.7
2792.294
River Rch & RM=HEWETTCK,Main      ,11657.1
3127.551
River Rch & RM=HEWETTCK,Main      ,9232.9
3744.751
River Rch & RM=HEWETTCK,Main      ,4863.9
3814.515
Boundary for River Rch & Prof#=HEWETTCK,Main      ,1
Up Type=0
Dn Type=3
Dn Slope=0.003091

--- HEWETTCK.g01 (geometry) ---

Geom Title=USGS 10m DEM
Program Version=4.10

River Reach=HEWETTCK        ,Main
Reach XY= 30
      1720200.85      346385.251     1720800.049      346728.334
     1720873.833      346889.792     1720846.924      347140.226
     1720923.007      347212.713     1721822.184      347744.132
     1722723.226      348893.958     1722807.427      349272.083
     1722363.504      349941.441     1722287.462      350261.233
     1722658.295      350706.962     1722716.629       351057.17
     1722668.712      351310.295      1723055.17      351724.045
      1723086.42      352021.962     1723295.795      352319.774
     1723749.962      352501.024     1723988.503        352272.9
     1724088.504      351973.941     1724278.087      351919.775
     1724574.962       352066.65     1724906.212      352672.379
     1725206.212      352882.795     1726916.103       352864.98
     1728221.837      353802.274     1728599.962      354425.087
     1728727.045      354513.629     1729693.712       354439.67
     1730627.045      354518.837     1731407.254      354293.837

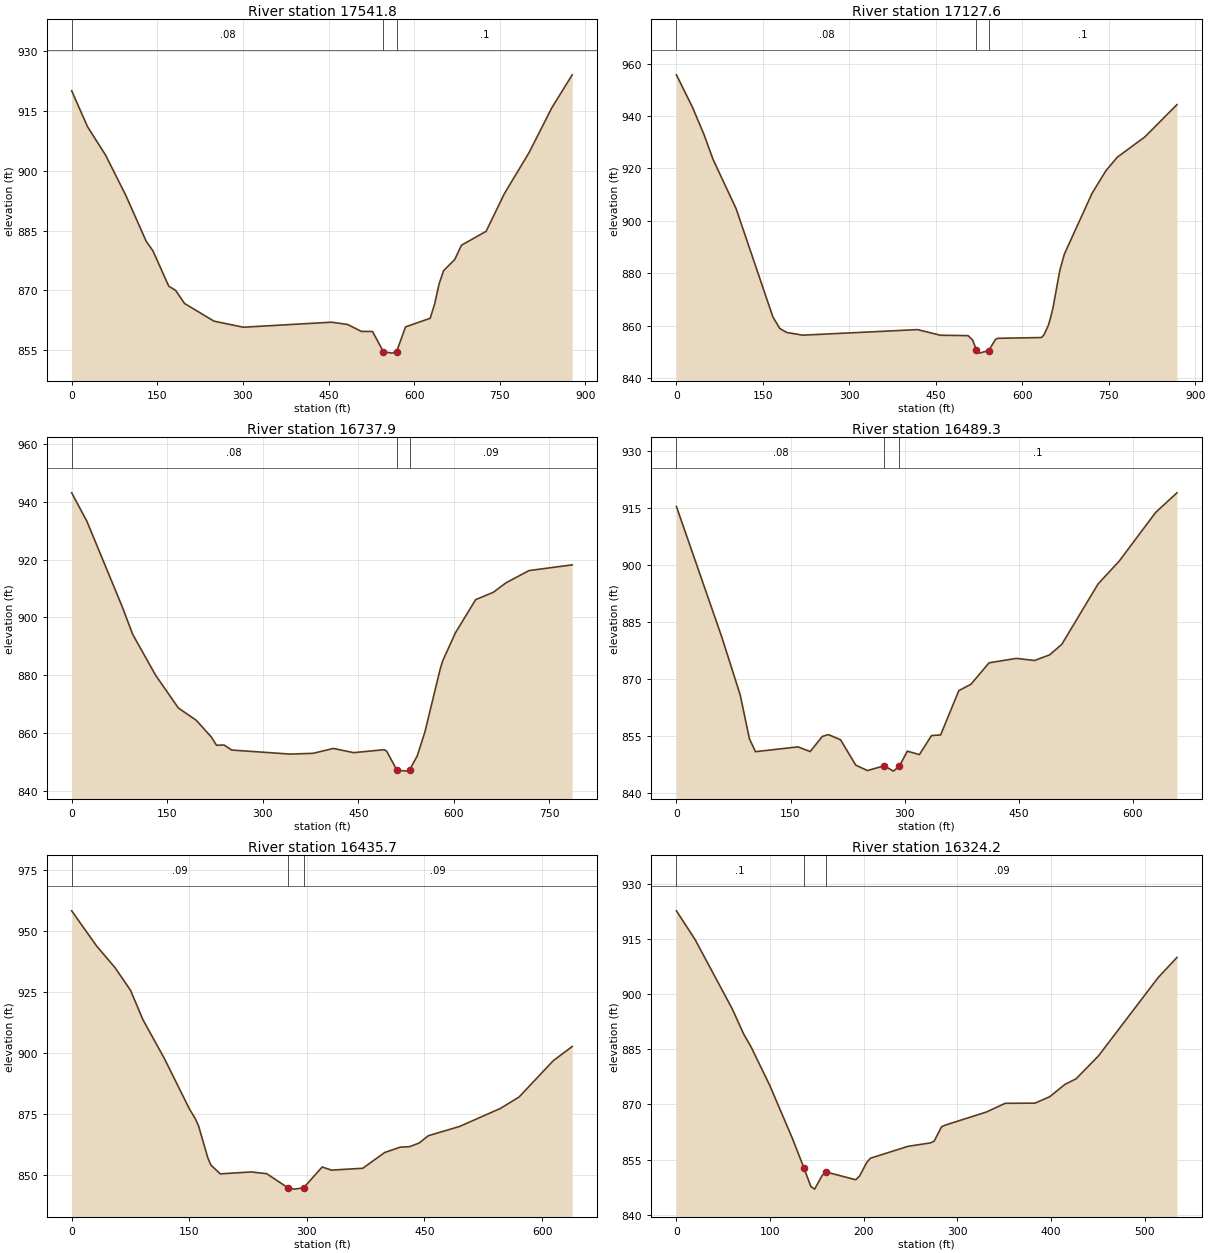
Type RM Length L Ch R = 1 ,17541.8 ,414.8,414.2,413.6
XS GIS Cut Line= 6
     1719949.791      346882.707     1720100.004      346568.606
     1720181.791      346418.237      1720200.85      346385.251
     1720283.319      346242.801     1720428.213      346188.379
#Sta/Elev= 30
       0     920    27.7  911.02    59.4  903.88      95  893.75   130.6  882.29
   142.4  879.89   170.1  871.05     182  870.02   197.8  866.72   249.3   862.3
   300.7  860.78   455.6  862.04   483.5  861.46   507.4  859.73     527  859.71
     546  854.65   561.4  854.29   569.2  854.67   584.9  860.87     628  863.02
   635.8  866.58   643.7  871.67   651.5  874.94   671.1  877.75   682.8  881.32
     726   884.8   757.8  894.19   801.4  904.56   841.1  915.74   876.8     924
#Mann= 3 , 0 , 0
       0     .08       0     546    .045       0   569.2      .1       0
Bank Sta=546,569.2
XS Rating Curve= 0 ,0
Exp/Cntr=0.3,0.1

Type RM Length L Ch R = 1 ,17127.6 ,381.5,389.7,397.6
XS GIS Cut Line= 2
     1720295.067       347073.26     1720708.227      346309.403
#Sta/Elev= 30
       0  955.72    27.9  943.33    47.8  932.97    63.7  923.37   103.6  904.64
   167.3   863.4   179.3  858.96   191.2  857.45   219.1   856.4   418.3  858.52
   458.1  856.37   505.9  856.23   513.9  854.56   520.4  850.83   525.8  849.55
   541.8  850.54   553.7  854.81   557.7   855.2   633.4   855.5   637.4  856.42
   645.4  860.18   649.3  863.21   653.3  866.78   665.3  881.23   673.2  887.39
     721  910.45   744.9  919.05   764.9   924.3   812.7  932.02   868.4  944.35
#Mann= 3 , 0 , 0
       0     .08       0   520.4    .045       0   541.8      .1       0
Bank Sta=520.4,541.8
XS Rating Curve= 0 ,0
Exp/Cntr=0.3,0.1

Type RM Length L Ch R = 1 ,16737.9 ,198,248.6,266.1
XS GIS Cut Line= 2
     1720472.506      347171.062     1721051.933      346640.463
#Sta/Elev= 30
       0  943.02    23.9  933.19    79.8  903.45    95.7   894.2   131.6   880.1
   167.5  868.74   195.4  864.53   219.4  858.68   227.3  855.89   239.3  855.96
   251.2  854.23     343  852.83   378.9   853.1   410.8  854.78   442.7  853.33
   490.5  854.35   494.5  853.82   510.5  847.29   526.4  846.95   530.4   847.4
   542.4  852.18   554.4  860.41   578.3  882.04   582.3  884.96   602.2  894.61
   634.1  906.14     662   908.7     682  911.98   717.9  916.18   785.7  918.15
#Mann= 3 , 0 , 0
       0     .08       0   510.5    .045       0   530.4     .09       0
Bank Sta=510.5,530.4
XS Rating Curve= 0 ,0
Exp/Cntr=0.3,0.1

Type RM Length L Ch R = 1 ,16489.3 ,51.7,53.6,65.9
XS GIS Cut Line= 5
     1720690.474      347181.652     1720858.659      347016.471
     1720866.298      347054.232     1720881.402      347079.232
      1721142.28      346839.338
#Sta/Elev= 30
       0  915.48    59.9  880.98    83.9  865.86    95.9  854.41   103.9  850.98
   159.8  852.24   175.8     851   191.8     855   199.8  855.47   215.8   854.1
   235.7  847.44   251.1  846.01   273.1  847.26   285.2  845.86   293.1  847.16
   303.5  851.12   319.4  850.21   335.3  855.22   347.3  855.38   371.2  867.04
   387.1  868.71     411  874.36   446.8  875.52   470.7  874.97   490.6  876.45
   506.6  879.24   554.3  895.12   582.2  901.16     630  913.94   657.9  919.08
#Mann= 3 , 0 , 0
       0     .08       0   273.1    .045       0   293.1      .1       0
Bank Sta=273.1,293.1
XS Rating Curve= 0 ,0
Exp/Cntr=0.3,0.1

Type RM Length L Ch R = 1 ,16435.7 ,162.6,111.5,82
XS GIS Cut Line= 4
     1720661.308      347260.038     1720831.664      347078.831
      1720860.96      347129.829     1721101.846       346903.05
#Sta/Elev= 30
       0  958.28    31.6  943.93    55.3  934.96      75  925.71    90.8  913.66
   118.4  897.58     150  877.09   157.9  872.86   161.9  869.98   173.7  856.86
   177.6  853.96   189.5  850.36     229  851.15   248.7  850.44   276.2  844.58
     284   844.1   295.8  844.64   319.5  853.18   331.4   851.9   371.3  852.66
   399.2  859.12   419.1  861.32   431.1  861.53     443  862.99     455  866.02
   494.9  869.83   546.7  877.19   570.6  881.88   614.4  896.85   638.4   902.6
#Mann= 3 , 0 , 0
       0     .09       0   276.2    .045       0   295.8     .09       0
Bank Sta=276.2,295.8
XS Rating Curve= 0 ,0
Exp/Cntr=0.3,0.1

Type RM Length L Ch R = 1 ,16324.2 ,598.3,592.8,587.2
XS GIS Cut Line= 2
     1720803.531      347292.878     1721185.599      346918.993
#Sta/Elev= 30
       0  922.69      20  914.84    59.8  895.92    71.8  889.18    79.8  885.62
    99.7  875.18   123.7  860.87   136.1  852.79   143.6  847.67   147.6  846.96
   155.6  850.63   159.6  851.64   191.5  849.51   195.5  850.48   203.5  854.31
   207.4  855.39   247.3   858.6   271.3  859.54   275.3  860.02   283.2  863.93
   287.2  864.38   331.1  867.94   351.1  870.31     383  870.36   398.9  872.13
   414.9  875.45   426.9  876.98   450.8  883.22   514.6  904.55   534.6     910
#Mann= 3 , 0 , 0
       0      .1       0   136.1    .045       0   159.6     .09       0
Bank Sta=136.1,159.6
XS Rating Curve= 0 ,0
Exp/Cntr=0.3,0.1

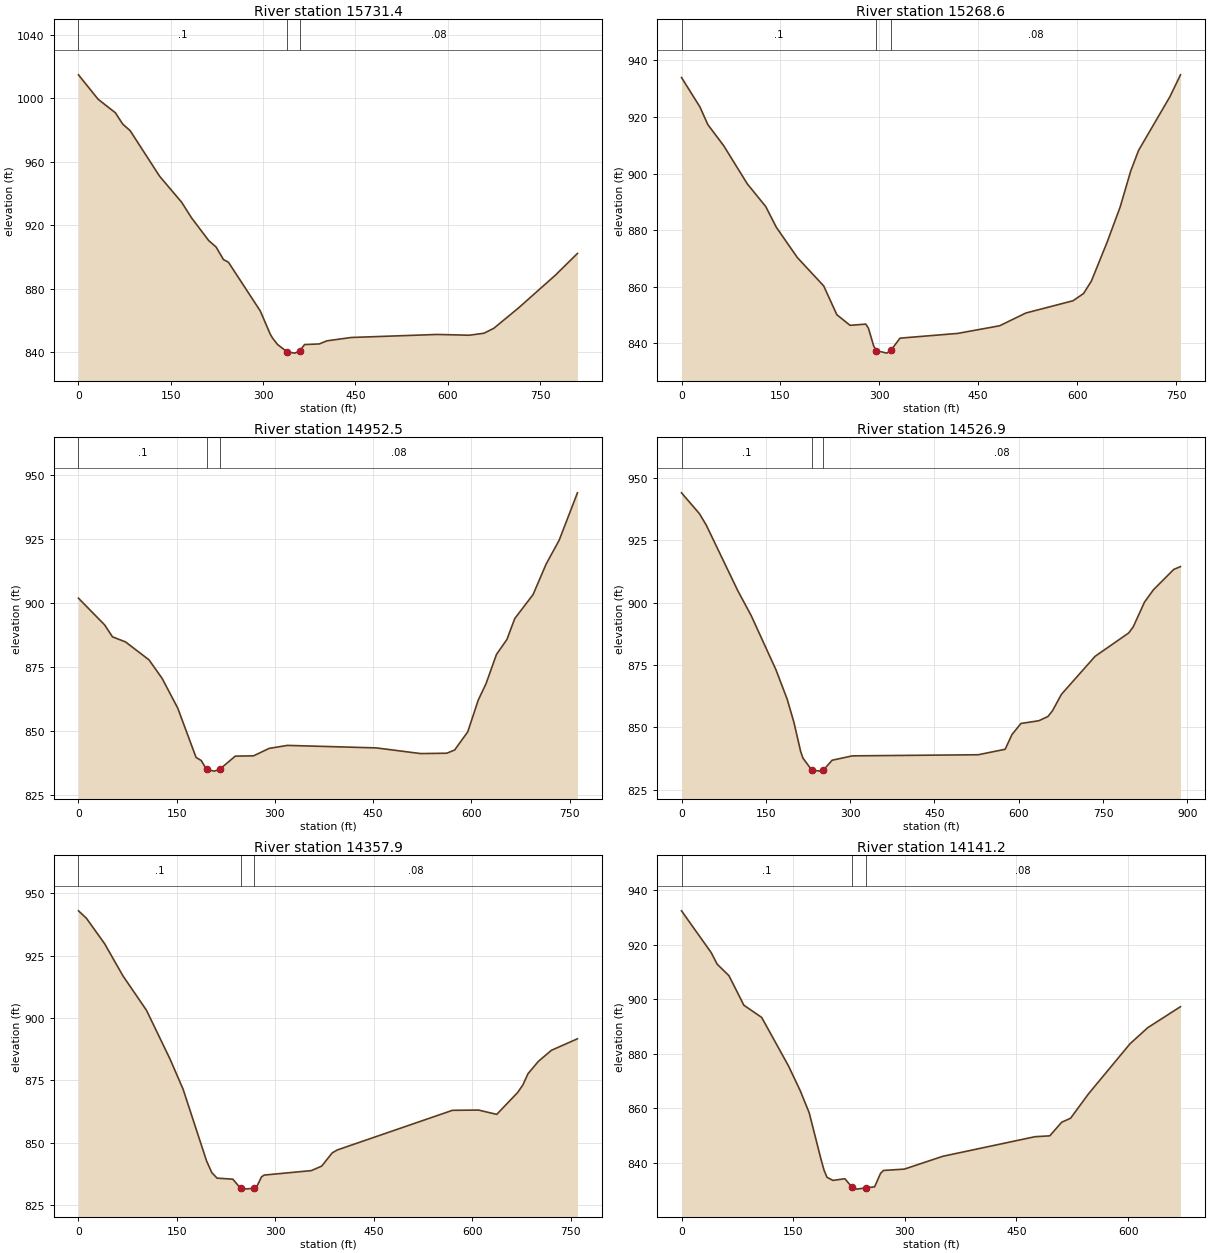
Type RM Length L Ch R = 1 ,15731.4 ,460.7,462.7,464.7
XS GIS Cut Line= 2
     1721233.503      347773.378     1721666.387      347087.868
#Sta/Elev= 30
       0  1014.9      32  999.46    59.9  991.02    71.9  983.84    83.9  979.74
   131.8     951   167.7  934.56   183.7  924.77   211.7   910.4   223.6  906.39
   235.6  898.46   243.6  896.83   295.5  866.03   311.5  851.54   315.5   848.9
   323.5  844.94   339.2  840.25   351.5   839.5   359.2  840.74   367.4  844.91
   391.4   845.3   403.4  847.22   443.3  849.36   583.1  851.27     635  850.78
     659  852.04     675  855.18   714.9  867.93   774.8  888.57   810.8  902.32
#Mann= 3 , 0 , 0
       0      .1       0   339.2    .045       0   359.2     .08       0
Bank Sta=339.2,359.2
XS Rating Curve= 0 ,0
Exp/Cntr=0.3,0.1

Type RM Length L Ch R = 1 ,15268.6 ,311.1,316.2,321.2
XS GIS Cut Line= 3
     1721621.247      347977.652       1721830.1      347700.024
      1722091.33      347384.892
#Sta/Elev= 30
       0  933.96      28  923.55    39.9  917.34    63.9   909.9    99.8  896.39
   127.8  888.35   143.8  881.05   175.7  870.34   215.6  860.34   235.6  850.15
   255.6   846.4   279.5  846.83   283.5  845.37   291.5  839.07   295.5  837.46
   311.5  836.58   318.4  837.83   331.4  841.87     419  843.55   482.5  846.25
   522.3  850.76   593.8  855.09   609.7  857.64   621.6  862.04   645.5  875.81
   665.3  888.26   681.2   900.9   693.2  908.23   740.8  927.24   756.7  934.92
#Mann= 3 , 0 , 0
       0      .1       0   295.5    .045       0   318.4     .08       0
Bank Sta=295.5,318.4
XS Rating Curve= 0 ,0
Exp/Cntr=0.3,0.1

Type RM Length L Ch R = 1 ,14952.5 ,422.3,425.6,428.7
XS GIS Cut Line= 2
     1721848.452      348114.276     1722417.601      347607.694
#Sta/Elev= 30
       0  901.92    39.9   891.5    51.9  886.82    71.8  884.84   107.7  877.82
   127.7  870.58   151.6  858.94   179.5   839.7   187.5  838.45   195.5  834.98
   207.4  834.32   215.4  834.99   239.4  840.18   267.3   840.3   291.2  843.21
   319.1  844.38   454.8   843.4   522.6  841.18   562.5  841.32   574.4  842.59
   594.4  849.68   610.4  862.07   622.3   868.5   638.3  879.96   654.2  885.78
   666.2  893.97   694.1  903.32   714.1  915.27     734  924.59   761.9  943.12
#Mann= 3 , 0 , 0
       0      .1       0   195.5    .045       0   215.4     .08       0
Bank Sta=195.5,215.4
XS Rating Curve= 0 ,0
Exp/Cntr=0.3,0.1

Type RM Length L Ch R = 1 ,14526.9 ,167.3,169,170.2
XS GIS Cut Line= 2
     1722092.384      348422.603     1722825.891      347922.386
#Sta/Elev= 30
       0  943.95      32  935.57      44  931.05     100  904.83     124  894.78
     168  873.13     188  861.34     200  852.06     212   840.4     216  837.76
     232  832.88     248  832.52     252  832.84     268  836.88   303.9  838.63
   527.9  839.08   575.9  841.28   587.9  847.13   603.9   851.6   635.9   852.7
   651.9  854.39   659.9  856.62   675.9  863.24   735.9  878.49   795.8  887.86
   803.8  890.32   823.8  900.19   839.8  905.15   875.8  913.27   887.8  914.41
#Mann= 3 , 0 , 0
       0      .1       0     232    .045       0     252     .08       0
Bank Sta=232,252
XS Rating Curve= 0 ,0
Exp/Cntr=0.3,0.1

Type RM Length L Ch R = 1 ,14357.9 ,217.8,216.6,215.4
XS GIS Cut Line= 3
     1722182.921      348544.032     1722685.308      348242.383
     1722854.579        348284.7
#Sta/Elev= 30
       0     943      12  940.06    39.9   929.8    67.8  916.92   103.6  903.16
   139.5   883.6   159.4  871.53   195.3   842.7   203.3  838.02   211.3  835.85
   235.2  835.44   247.2  831.75   251.1  831.45   267.1  831.76   271.1  832.12
     279  836.38     283  837.08   354.8  838.87   370.7  840.68   386.7  845.98
   394.6  847.16     570  863.04   609.8  863.14   637.5  861.41   669.3  870.16
   677.2  873.15   685.1   877.7     701  882.67   720.8  887.09   760.5  891.71
#Mann= 3 , 0 , 0
       0      .1       0   247.2    .045       0   267.1     .08       0
Bank Sta=247.2,267.1
XS Rating Curve= 0 ,0
Exp/Cntr=0.3,0.1

Type RM Length L Ch R = 1 ,14141.2 ,223.1,228.6,233.7
XS GIS Cut Line= 2
     1722336.201      348715.266     1722892.334      348340.887
#Sta/Elev= 30
       0  932.53    39.9  917.19    47.9  912.95    63.8   908.7    83.8  897.88
   107.7  893.41   143.7  875.62   159.6  866.47   171.6  858.36   187.6  841.16
   191.5  837.32   195.5  834.72   203.5  833.58   219.5  834.19   228.6  831.26
   235.4  830.38   247.4  830.84   259.4  831.21   267.4  836.17   271.4  837.24
   299.3  837.72   351.2  842.44   474.9  849.62   494.8  849.94   510.8  854.94
   522.8  856.41   546.7  865.31   602.6  883.73   626.5  889.65   670.4  897.34
#Mann= 3 , 0 , 0
       0      .1       0   228.6    .045       0   247.4     .08       0
Bank Sta=228.6,247.4
XS Rating Curve= 0 ,0
Exp/Cntr=0.3,0.1

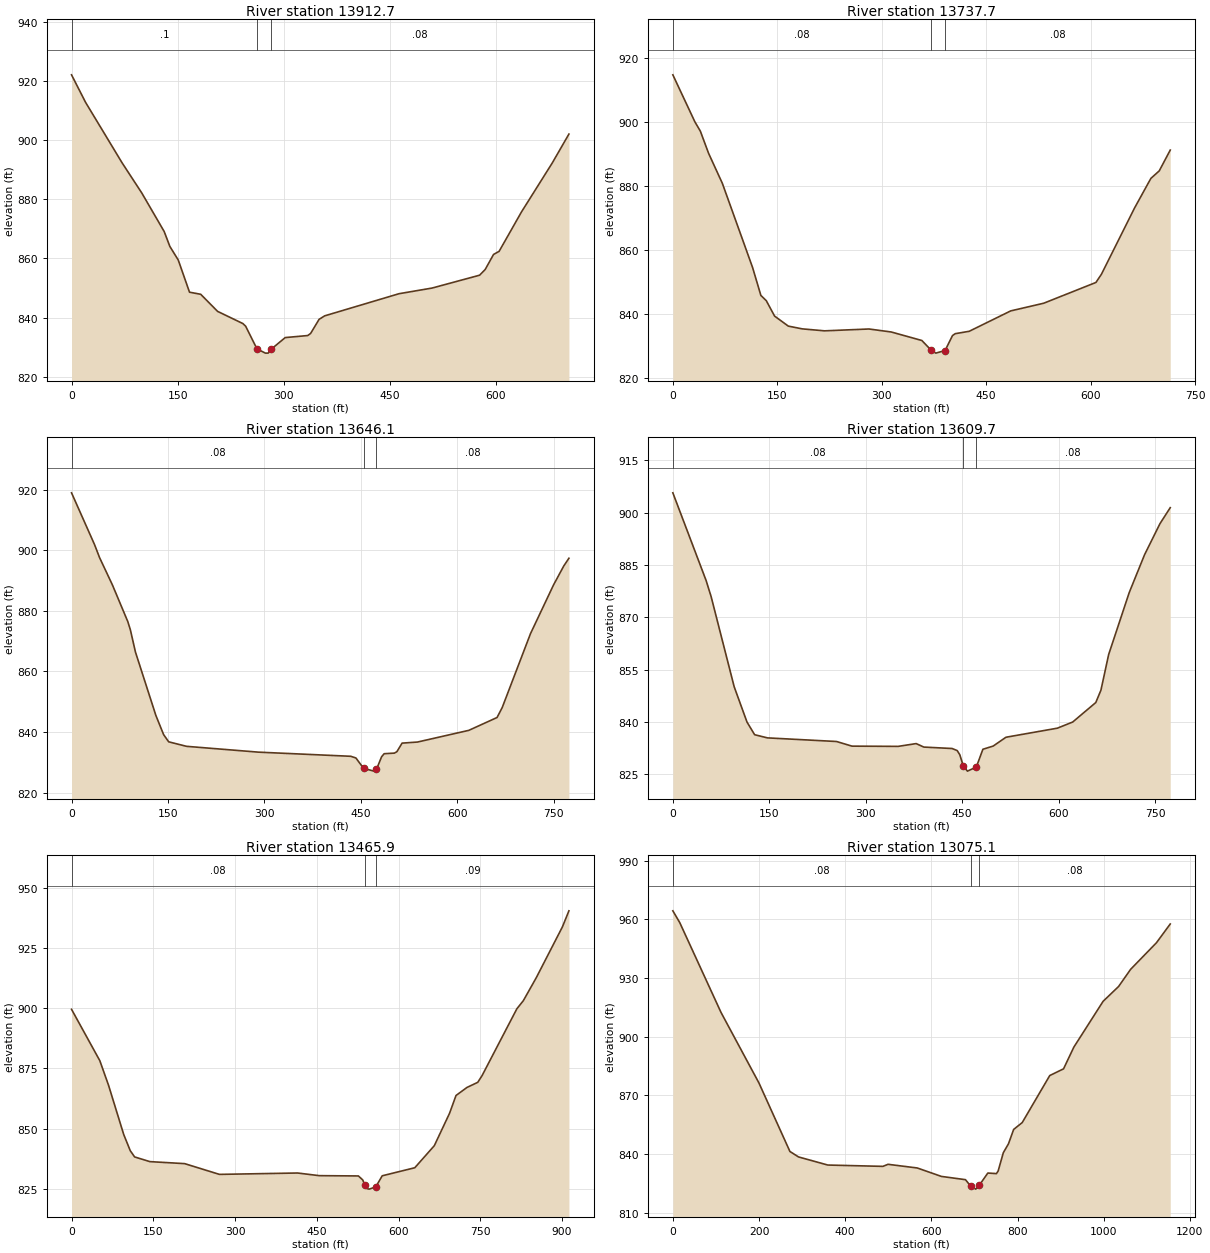
Type RM Length L Ch R = 1 ,13912.7 ,169.7,174.9,180.3
XS GIS Cut Line= 5
      1722376.19      348820.402      1722616.57      348790.801
     1722746.093      348738.499     1722841.291      348687.192
     1722963.346      348512.355
#Sta/Elev= 30
       0  922.01    19.8  912.73    71.5  892.28    99.3  882.11     131  869.08
     139  864.05   150.9  859.45   166.8  848.59   182.6  847.89   206.5  842.11
   242.2     838   246.2  837.09   262.2  829.43   274.1  828.01   278.1  828.02
   282.1   829.3   302.1  833.26     334  833.95     338  834.66     350  839.42
   357.9   840.6     463  848.08   509.8  849.99   576.9  854.33   584.8  856.25
   596.6  861.33   604.5  862.39   636.1  875.69   679.6  892.22   703.2     902
#Mann= 3 , 0 , 0
       0      .1       0   262.2    .045       0   282.1     .08       0
Bank Sta=262.2,282.1
XS Rating Curve= 0 ,0
Exp/Cntr=0.3,0.1

Type RM Length L Ch R = 1 ,13737.7 ,93.7,91.6,89.5
XS GIS Cut Line= 4
     1722370.118      348903.462     1722524.285      348964.573
     1722811.785      348915.268     1723054.146      348830.545
#Sta/Elev= 30
       0  914.71    31.6  900.02    39.5  897.09    51.3  890.17    71.1  880.76
   114.5  854.44   126.4  845.71   134.2  844.05   146.1  839.24   165.8   836.1
   185.8  835.24   217.8  834.62   281.7   835.2   313.7  834.26   357.6   831.6
     371  828.56   377.6  827.65     391  828.47   401.6  833.14   405.6  833.74
   425.6  834.48   485.2  840.86   532.6  843.26   607.6  849.76   615.5  852.33
   662.9  872.99   682.7  880.82   686.6  882.33   698.5  884.66   714.3  891.17
#Mann= 3 , 0 , 0
       0     .08       0     371    .045       0     391     .08       0
Bank Sta=371,391
XS Rating Curve= 0 ,0
Exp/Cntr=0.3,0.1

Type RM Length L Ch R = 1 ,13646.1 ,36.4,36.4,36.4
XS GIS Cut Line= 3
     1722315.257      349008.323     1722527.063      349077.073
     1723060.396      348938.879
#Sta/Elev= 30
       0  918.99    35.8  901.88    43.7  897.54    63.6  888.56    87.5  876.46
    91.5  873.75    99.4   866.4   131.2  845.44   143.2  839.13   151.1  836.74
   178.9  835.25   290.6  833.33   434.3  831.96   442.3   831.4   454.2     828
   470.2  827.06   474.2   827.6   482.2  831.78   486.2  832.81   502.2  833.01
   506.1   833.5   514.1  836.31   538.1  836.67   617.9  840.53   661.8  844.77
   669.8  848.04   713.8  872.46   749.7  888.58   765.6  894.84   773.6  897.38
#Mann= 3 , 0 , 0
       0     .08       0   454.2    .045       0   474.2     .08       0
Bank Sta=454.2,474.2
XS Rating Curve= 0 ,0
Exp/Cntr=0.3,0.1

Type RM Length L Ch R = 1 ,13609.7 ,139.1,143.8,148.5
XS GIS Cut Line= 3
     1722326.368      349043.045     1722538.174      349111.795
     1723071.507      348973.601
#Sta/Elev= 30
       0  905.72    51.7  880.58    59.6   875.9    95.4  850.07   115.3  839.96
   127.2  836.32   147.1  835.41   254.6  834.37   278.6  833.04   350.4  832.97
   378.4  833.77   390.4  832.77   434.3  832.36   442.3  831.76   446.3  830.57
     452  827.22   458.2  825.87     472  827.04   482.2  832.14   498.2  833.06
   518.1  835.59     598  838.19   621.9  839.96   657.8  845.55   665.8  849.09
   677.8  859.31   709.8   877.1   733.7  887.98   757.7   896.9   773.6  901.46
#Mann= 3 , 0 , 0
       0     .08       0     452    .045       0     472     .08       0
Bank Sta=452,472
XS Rating Curve= 0 ,0
Exp/Cntr=0.3,0.1

Type RM Length L Ch R = 1 ,13465.9 ,376.5,390.7,404.9
XS GIS Cut Line= 3
     1722281.295      349118.458     1722489.089      349211.214
     1723172.682      349165.642
#Sta/Elev= 30
       0  899.56    51.9  878.24    67.9  868.04    95.8  847.57   107.8  840.86
   115.8  838.28   143.7  836.34   207.6   835.5   271.4  831.04   414.8  831.61
   454.6  830.51   526.3  830.39   534.3  828.76   538.2  826.64   542.2  825.14
   546.2  824.92   558.2  825.83   570.1  830.45   629.9   833.8   665.7  842.96
   693.6  856.37   705.5  863.78   725.5  867.11   745.4  869.25   753.3  872.03
   817.1  899.75     829  903.13   852.9  912.73   900.7  933.75   912.7  940.44
#Mann= 3 , 0 , 0
       0     .08       0   538.2    .045       0   558.2     .09       0
Bank Sta=538.2,558.2
XS Rating Curve= 0 ,0
Exp/Cntr=0.3,0.1

Type RM Length L Ch R = 1 ,13075.1 ,297.1,294.4,291.8
XS GIS Cut Line= 3
      1722053.43      349111.947     1722295.618       349338.51
     1723019.576      349729.135
#Sta/Elev= 30
       0  964.29      16  958.28   111.9  912.31   199.8  876.31   271.7  841.29
   291.7   838.5   359.6  834.36   487.4  833.68   499.4  834.73   567.2  832.86
   623.2  828.55   679.1  826.88     691  823.64     703  822.05     711  823.98
     731  830.27   750.9  829.98   754.9   831.3   766.9  840.65   778.9  845.22
   790.9  852.55   810.8  856.07   874.7   880.1   906.7  883.53   930.6  894.63
   998.5  918.04  1034.5  925.63  1062.4   934.4  1122.3  947.98  1154.3  957.56
#Mann= 3 , 0 , 0
       0     .08       0     691    .045       0     711     .08       0
Bank Sta=691,711
XS Rating Curve= 0 ,0
Exp/Cntr=0.3,0.1

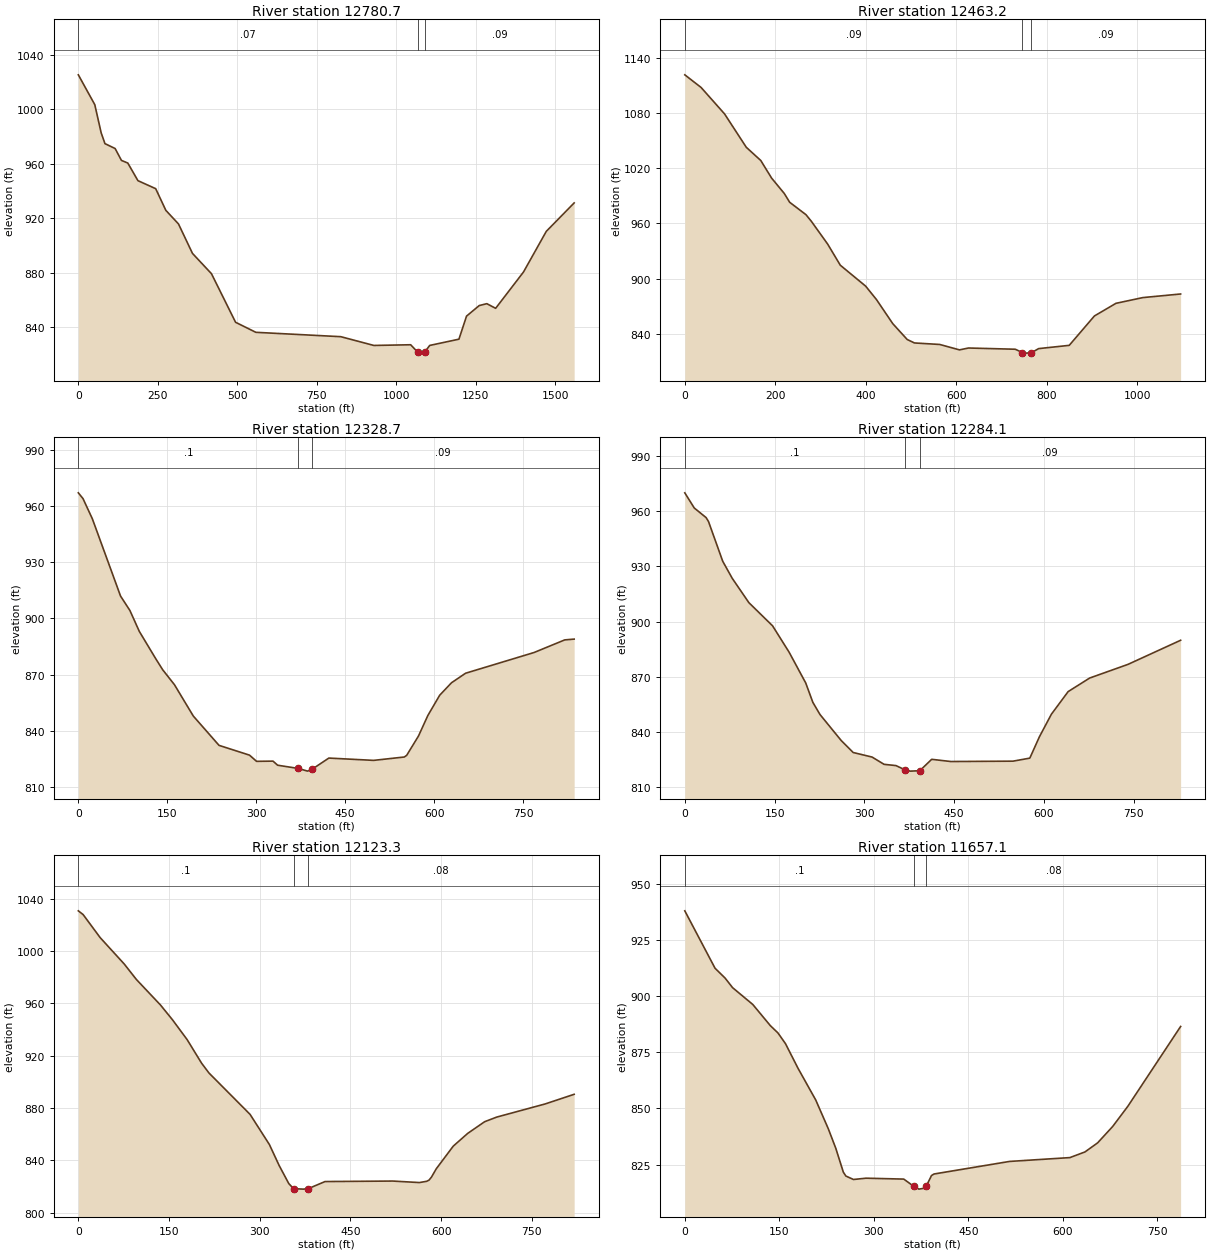
Type RM Length L Ch R = 1 ,12780.7 ,329.9,317.5,303.7
XS GIS Cut Line= 4
      1721604.31      349141.305     1722237.458      349671.192
     1722610.722      349824.187     1722939.498       349790.55
#Sta/Elev= 30
       0 1025.38    51.8 1003.44    71.8  982.79    83.8  974.82   115.7  971.24
   135.6   962.5   155.6  960.57   187.5  947.62   243.3  941.74   275.2  925.83
   315.1  915.79     359  894.19   418.8  879.25   494.6  843.57   558.4   836.2
   825.6  832.99   929.5  826.55  1045.3  827.06  1066.8  821.78  1073.3  820.91
  1089.2   821.6  1105.2  826.56  1197.1  831.15    1221  848.09  1260.9  855.85
  1284.8  857.24  1312.6  853.84  1400.2  880.52  1471.9  910.39  1559.5  931.27
#Mann= 3 , 0 , 0
       0     .07       0  1066.8    .045       0  1089.2     .09       0
Bank Sta=1066.8,1089.2
XS Rating Curve= 0 ,0
Exp/Cntr=0.3,0.1

Type RM Length L Ch R = 1 ,12463.2 ,114.6,134.6,143.3
XS GIS Cut Line= 4
     1721636.862      350332.712     1722097.701      350059.864
     1722454.472       350032.52      1722640.67      349953.093
#Sta/Elev= 30
       0 1121.58      36 1107.85    87.9 1079.08   135.9 1042.82   167.9 1028.46
   191.8 1009.35   219.8  992.63   231.8  983.04   267.8  969.54   279.8  962.28
   315.7  937.61   343.7   914.6   399.7  891.87   423.6  877.28   459.6   851.1
   491.6  833.82   507.6   830.1   563.4  828.45   607.1  822.58     627   824.6
   730.4  823.27   746.3  819.58   754.2  819.04   766.2  819.48     782  823.95
   849.6  827.49   905.3  859.44   952.9  873.18  1012.4  879.42  1095.8  883.33
#Mann= 3 , 0 , 0
       0     .09       0   746.3    .045       0   766.2     .09       0
Bank Sta=746.3,766.2
XS Rating Curve= 0 ,0
Exp/Cntr=0.3,0.1

Type RM Length L Ch R = 1 ,12328.7 ,53.4,44.5,48
XS GIS Cut Line= 5
     1721947.961      350302.052     1722244.836      350144.499
     1722268.925      350169.239     1722307.987      350176.835
     1722687.545      349984.343
#Sta/Elev= 30
       0  967.03     7.9  963.94    23.7  953.12    71.2  911.89      87  904.19
   102.8  893.04   130.5  878.46   142.3  872.52   162.1  864.56   193.8  847.86
   237.2  832.18   288.6  826.96   300.5  823.65   328.2  823.76   336.1  821.57
     371  819.85   386.5  818.42   394.5   819.5   422.4  825.39   497.9  824.16
   549.6  825.96   553.6  826.84   573.5  837.15   589.4  848.17   609.3  858.95
   629.2  865.61     653   870.7   768.4  881.76   820.1  888.49     836  888.92
#Mann= 3 , 0 , 0
       0      .1       0     371    .045       0   394.5     .09       0
Bank Sta=371,394.5
XS Rating Curve= 0 ,0
Exp/Cntr=0.3,0.1

Type RM Length L Ch R = 1 ,12284.1 ,186.4,160.8,135.4
XS GIS Cut Line= 4
     1721944.706      350343.284     1722226.607      350198.536
     1722310.158      350224.578     1722684.289      350025.576
#Sta/Elev= 30
       0     970    15.8  961.76    35.6  956.53    39.6   954.4    63.4  932.76
    79.2  923.54     107   910.3   146.6  897.69   174.3  883.32     202  866.61
   213.9  856.08   225.8  849.47   261.4  835.27   281.2  828.81   312.9  826.32
   332.8  822.38   352.7  821.69   368.6  819.28   376.6  818.68   392.5  818.89
   412.4   825.1   444.4   823.9   548.3   824.1   576.3  825.75   592.3  837.33
   612.3   849.6   640.3  861.91   676.3   869.3   740.2  876.71   828.2  889.83
#Mann= 3 , 0 , 0
       0      .1       0   368.6    .045       0   392.5     .09       0
Bank Sta=368.6,392.5
XS Rating Curve= 0 ,0
Exp/Cntr=0.3,0.1

Type RM Length L Ch R = 1 ,12123.3 ,456.3,466.2,475.9
XS GIS Cut Line= 2
     1722068.047      350584.036      1722703.63      350065.934
#Sta/Elev= 30
       0 1030.84       8 1027.94      36 1010.41      76  990.12      96  978.35
     136  958.75     156  947.35     180   932.3     204  914.22     216  906.85
     284  875.19     316  852.11     332  836.19     348  822.29     356  818.35
     372  818.01     380  818.32     408   823.8     520  824.18     564  823.03
     576  823.98     580   824.9     584  827.18     592  833.59     620  850.87
     644  860.65     672  869.58     692  873.11     772  883.14     820  890.53
#Mann= 3 , 0 , 0
       0      .1       0     356    .045       0     380     .08       0
Bank Sta=356,380
XS Rating Curve= 0 ,0
Exp/Cntr=0.3,0.1

Type RM Length L Ch R = 1 ,11657.1 ,235.9,241,246.1
XS GIS Cut Line= 2
     1722300.286      350811.475     1723053.014      350581.322
#Sta/Elev= 30
       0  937.88      48  912.36    63.9     908    75.9  903.71   107.9  896.25
   135.8  886.83   147.8  883.61   159.8  878.84   179.8  867.84   207.8  853.81
   227.8  840.99   239.7   832.3   251.7  821.68   255.7  819.96   267.7  818.43
   287.7     819   347.6   818.6   363.6  815.36   371.6  814.14   379.6  814.51
   383.6  815.59   391.6  820.18   395.6  820.86   515.4  826.45   611.3  828.16
   635.3  830.68   655.3   834.7   679.2  841.98   703.2  850.92   787.1  886.46
#Mann= 3 , 0 , 0
       0      .1       0   363.6    .045       0   383.6     .08       0
Bank Sta=363.6,383.6
XS Rating Curve= 0 ,0
Exp/Cntr=0.3,0.1

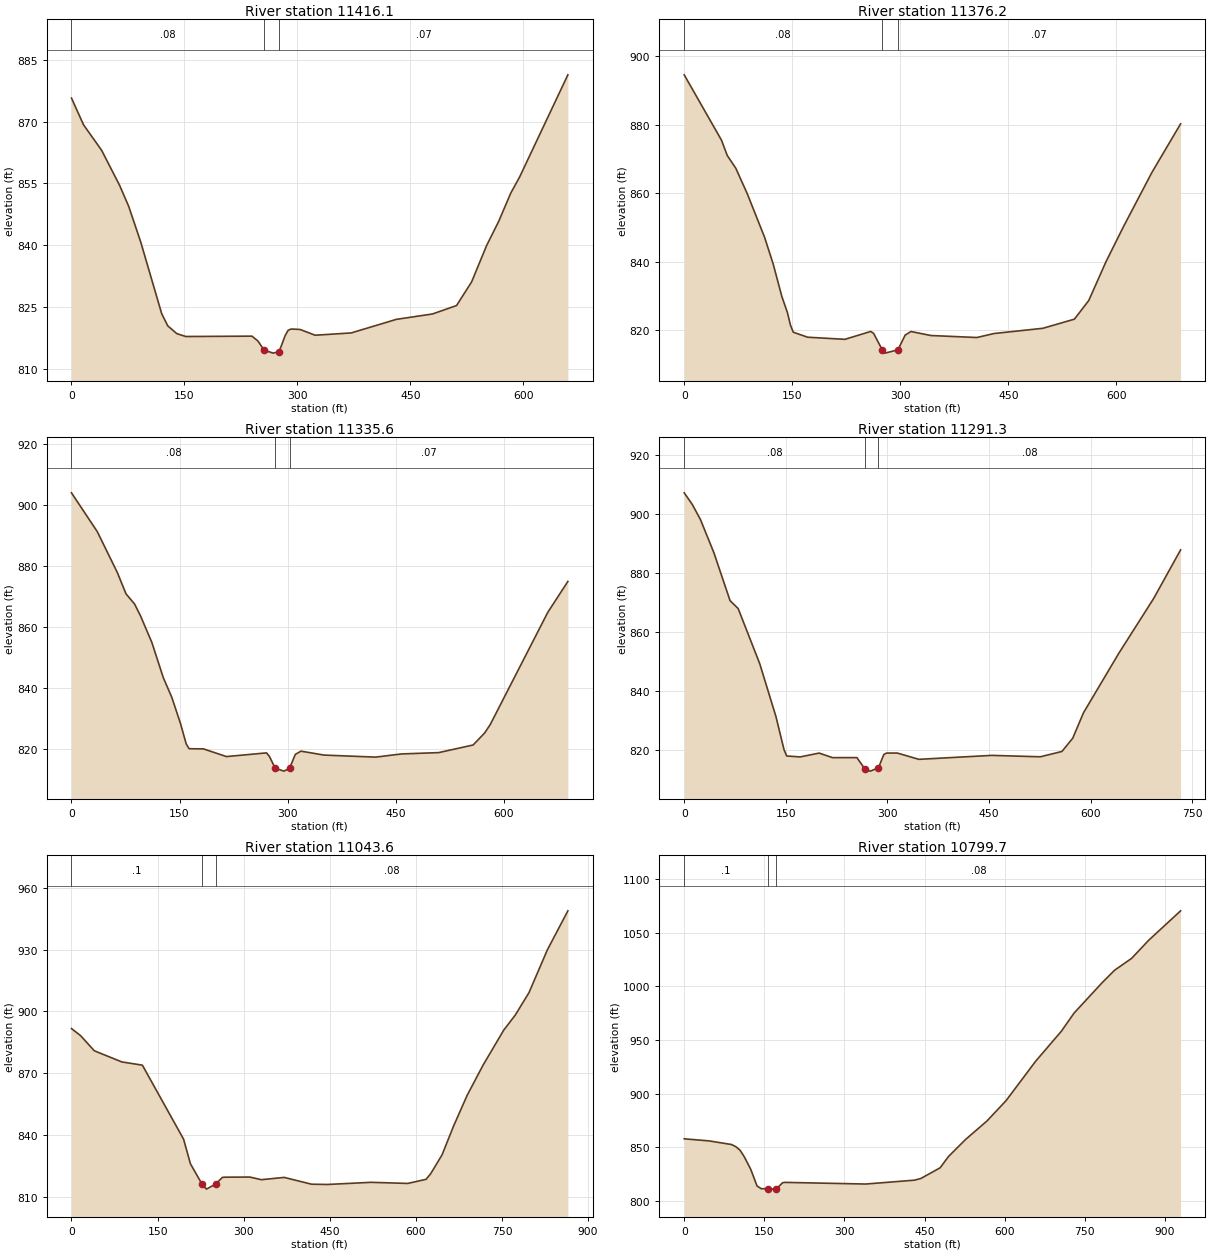
Type RM Length L Ch R = 1 ,11416.1 ,40.8,39.9,38.9
XS GIS Cut Line= 2
     1722449.848      350956.141     1723106.315      350898.633
#Sta/Elev= 30
       0   875.7      16  869.22    39.9  863.07    63.9  854.53    75.9  849.47
    91.9  840.81   119.8  823.39   127.8  820.46   139.8  818.57   151.8  817.87
   239.6  817.96   247.6  816.77   255.6   814.6   267.6  813.84   275.6  814.17
   283.6  818.06   287.6  819.37   291.6  819.69   303.5  819.58   323.5  818.18
   371.4  818.74   431.3  822.03   479.3  823.34   511.2  825.38   531.2  831.11
   551.2  839.97   567.1  845.77   583.1  852.62   595.1  856.62     659  881.34
#Mann= 3 , 0 , 0
       0     .08       0   255.6    .045       0   275.6     .07       0
Bank Sta=255.6,275.6
XS Rating Curve= 0 ,0
Exp/Cntr=0.3,0.1

Type RM Length L Ch R = 1 ,11376.2 ,40.6,40.5,40.6
XS GIS Cut Line= 2
     1722429.515      351009.083     1723113.109      350922.277
#Sta/Elev= 30
       0  894.56    51.8  875.46    59.8  870.99    71.7  867.26    87.6  859.81
   111.5  847.17   123.5  839.34   135.4  829.94   143.4  825.06   147.4  821.54
   151.4   819.4   171.3  817.94   223.1  817.32   258.9  819.62   262.9  819.07
   274.8  814.31   278.8  813.29   296.7  814.25   306.7  818.54   314.7   819.6
   342.6  818.43   406.3  817.85   430.2  819.02   497.9  820.54   541.7  823.21
   561.6  828.65   585.5  839.97   609.4  850.06   649.2  866.03   689.1  880.25
#Mann= 3 , 0 , 0
       0     .08       0   274.8    .045       0   296.7     .07       0
Bank Sta=274.8,296.7
XS Rating Curve= 0 ,0
Exp/Cntr=0.3,0.1

Type RM Length L Ch R = 1 ,11335.6 ,43.5,44.3,45.3
XS GIS Cut Line= 2
     1722425.175      351050.315     1723108.769       350963.51
#Sta/Elev= 30
       0  903.95    35.8  891.24    63.7   877.8    75.7  870.85    87.6   867.5
    95.6  863.75   111.5  854.96   127.5  843.36   139.4  836.85   151.4  828.29
   159.3  821.64   163.3  820.08   183.2  820.03   215.1  817.51   270.8  818.72
   274.8  817.54   282.8  813.71   294.8  812.74   302.7  813.63   310.7  818.22
   318.6  819.29   350.5     818   422.2  817.33   458.1  818.37   509.8  818.81
   557.6  821.31   573.6  825.25   581.5  828.08   661.2  864.77   689.1  874.91
#Mann= 3 , 0 , 0
       0     .08       0   282.8    .045       0   302.7     .07       0
Bank Sta=282.8,302.7
XS Rating Curve= 0 ,0
Exp/Cntr=0.3,0.1

Type RM Length L Ch R = 1 ,11291.3 ,251.7,247.7,243.6
XS GIS Cut Line= 2
     1722440.083      351082.009     1723170.334       351017.99
#Sta/Elev= 30
       0  907.33      12  903.36    23.9  898.31    43.8  887.04    67.7  870.78
    79.7  868.07   107.6   851.7   111.6  849.34   135.5  831.43   147.4  820.23
   151.4  818.08   171.3  817.77   199.2  819.07   219.1  817.52     255  817.54
   266.9  813.67   274.9  812.95   286.8  814.08   294.8  818.59   298.8  819.07
   314.7  819.08   346.6  816.95   454.2  818.29   525.9  817.81   557.8  819.62
   573.7   824.1   589.6  832.73   641.4  852.78   693.2  871.49     733  887.98
#Mann= 3 , 0 , 0
       0     .08       0   266.9    .045       0   286.8     .08       0
Bank Sta=266.9,286.8
XS Rating Curve= 0 ,0
Exp/Cntr=0.3,0.1

Type RM Length L Ch R = 1 ,11043.6 ,245.2,243.9,242.5
XS GIS Cut Line= 2
     1722436.026      351347.624     1723274.784      351137.121
#Sta/Elev= 30
       0  891.68    15.9  888.24    39.8  880.88    87.7  875.46   123.5  873.89
   195.3   837.9   207.2  825.94   227.2  816.13   235.1  813.59   251.1  816.04
     263  819.31     267   819.4   310.8  819.46   330.8  818.18   370.6  819.29
   418.4  815.98   446.3  815.86     522   816.9   585.8  816.36   617.7  818.35
   625.7  821.04   645.6  830.26   665.5  844.16   689.4  859.26   717.3  874.03
   753.2  890.99   773.1  898.23     797  909.14   828.9  929.87   864.8  948.96
#Mann= 3 , 0 , 0
       0      .1       0   227.2    .045       0   251.1     .08       0
Bank Sta=227.2,251.1
XS Rating Curve= 0 ,0
Exp/Cntr=0.3,0.1

Type RM Length L Ch R = 1 ,10799.7 ,125,92.1,68.7
XS GIS Cut Line= 3
     1722644.359      351482.173     1722714.888      351521.236
     1723525.435      351269.499
#Sta/Elev= 30
       0  857.99    46.1  856.08    88.6  852.69    96.6   850.7   104.5   847.4
   112.5  841.26   124.5  829.71   136.4  814.04   144.4  811.52   156.3  811.57
   168.3  811.15   172.3  811.29   184.2   817.1   188.2  817.44   339.6  815.89
   431.3  819.49   443.2  821.09   479.1  830.98     495   841.6   526.9  857.42
   566.8  874.57   602.6  893.52   658.4  930.46   706.2  958.18   730.1  975.14
   781.9 1003.02   805.8 1014.94   837.7    1026   869.6 1042.81   929.4 1070.25
#Mann= 3 , 0 , 0
       0      .1       0   156.3    .045       0   172.3     .08       0
Bank Sta=156.3,172.3
XS Rating Curve= 0 ,0
Exp/Cntr=0.3,0.1

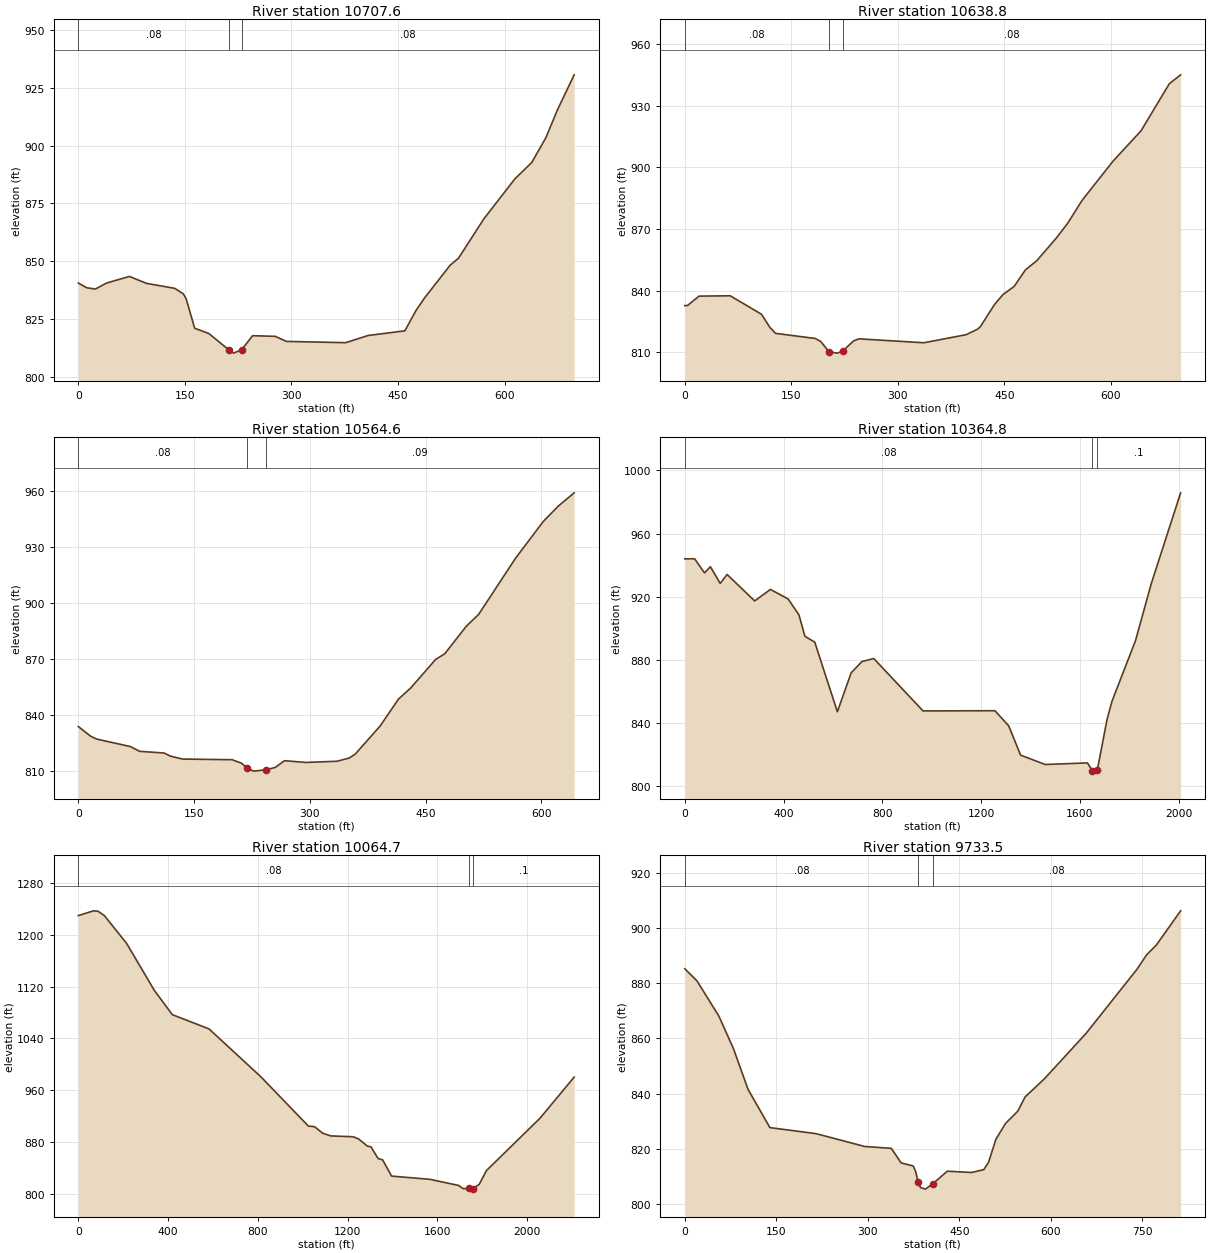
Type RM Length L Ch R = 1 ,10707.6 ,56.3,68.7,57.4
XS GIS Cut Line= 4
      1722661.72      351593.935     1722849.437      351598.276
     1722851.607      351540.767     1723289.975       351427.92
#Sta/Elev= 30
       0  840.58      12  838.51      24  837.98      40   840.6    71.9  843.43
    95.9  840.44   135.8  838.27   147.8   835.9   151.8  833.76   163.8  821.03
   183.8  818.72   211.8  811.71   218.5  810.26     230  811.75   245.3   817.8
   277.1  817.52     293  815.33   376.4  814.78   408.1   817.9   459.7   819.9
   475.6  828.83   487.5  834.16   523.3  848.25   535.2  851.32   570.9  868.35
   614.6  885.63   638.4  892.75   658.3   903.5   674.2  915.28     698  930.63
#Mann= 3 , 0 , 0
       0     .08       0   211.8    .045       0     230     .08       0
Bank Sta=211.8,230
XS Rating Curve= 0 ,0
Exp/Cntr=0.3,0.1

Type RM Length L Ch R = 1 ,10638.8 ,44.3,74.2,119.7
XS GIS Cut Line= 4
     1722714.888      351626.487     1722902.605      351630.828
     1722904.776      351573.319     1723343.144      351460.472
#Sta/Elev= 30
       0  832.65       4  832.75      20  837.29    63.9  837.46   107.9  828.49
   119.8  822.06   127.8  819.16   183.8  816.66   191.6  815.13   203.1  810.19
   214.6  809.53   222.3  810.53   237.6  815.48   245.3  816.49   336.6  814.58
   396.2  818.52   412.1   821.2   416.1  822.42   435.9  833.16   447.8  838.01
   463.7  842.05   479.6  850.11   495.5  854.54   523.3   865.7   539.2  872.87
     559  883.81   602.7  902.96   642.4  917.87   682.1  940.74     698  945.07
#Mann= 3 , 0 , 0
       0     .08       0   203.1    .045       0   222.3     .08       0
Bank Sta=203.1,222.3
XS Rating Curve= 0 ,0
Exp/Cntr=0.3,0.1

Type RM Length L Ch R = 1 ,10564.6 ,201.4,199.9,197
XS GIS Cut Line= 4
     1722726.824      351656.869     1722833.161      351670.975
     1723094.663      351637.338     1723342.059      351525.576
#Sta/Elev= 30
       0  833.97    15.9   828.8    23.8  827.27    67.5  823.26    79.5  820.72
   111.3  819.81   119.2  818.17   135.2  816.58   199.2  816.24   211.1  814.43
   219.1  811.71   227.1  810.14   243.1  810.85   255.1   812.1   267.1  815.72
     295  814.78     335  815.41     351  817.13   358.9  819.29   390.9  834.19
   414.8  848.64   430.8  854.64   462.8  869.76   474.7  872.83   502.7  887.56
   518.6  893.84   566.5  923.92   602.5  943.59   622.4  951.94   642.4  958.83
#Mann= 3 , 0 , 0
       0     .08       0   219.1    .045       0   243.1     .09       0
Bank Sta=219.1,243.1
XS Rating Curve= 0 ,0
Exp/Cntr=0.3,0.1

Type RM Length L Ch R = 1 ,10364.8 ,320.6,300.1,279.2
XS GIS Cut Line= 5
     1721464.349      351779.791     1722641.432      351696.458
     1722761.546      351795.758      1723123.96      351801.184
     1723408.248      351678.571
#Sta/Elev= 30
       0  943.96    39.9  944.03    79.7  935.08   103.6  938.99   143.5   928.4
   171.4  934.07     283  917.29   346.8  924.61   418.6  918.52   462.4  908.42
   486.4  894.89   526.2  891.18   617.9  847.04   673.7   871.7   717.6   878.9
   765.4  880.77   964.8  847.56    1256  847.68  1311.9  838.07  1359.8  819.54
  1459.4  813.59  1630.6   814.6  1650.5  809.72  1666.5  809.39  1670.4  809.93
  1710.2  842.32  1730.1  853.74  1825.4   892.2  1888.8  928.12  2007.9  985.84
#Mann= 3 , 0 , 0
       0     .08       0  1650.5    .045       0  1670.4      .1       0
Bank Sta=1650.5,1670.4
XS Rating Curve= 0 ,0
Exp/Cntr=0.3,0.1

Type RM Length L Ch R = 1 ,10064.7 ,337.5,331.2,324.8
XS GIS Cut Line= 3
     1721812.603      353185.392     1722765.296      352442.306
     1723480.825      351742.187
#Sta/Elev= 30
       0 1229.62    67.8 1236.96    87.7 1236.34   115.6 1229.73   215.3 1186.59
   338.9 1114.03   418.7 1076.64   582.2 1054.64   813.5  980.65  1024.8  904.65
  1052.7  903.57  1088.6  893.59  1124.5  889.41  1224.2  888.08  1248.1  884.86
    1288  873.64  1303.9  872.47  1335.8  854.43  1355.8  852.46  1395.7  827.36
  1567.2  822.31  1694.8  812.86  1714.7   807.9  1738.7  808.29  1750.6  807.21
  1758.6  808.12  1786.5  814.62  1818.4  835.86  2057.7  916.89  2209.3  980.21
#Mann= 3 , 0 , 0
       0     .08       0  1738.7    .045       0  1758.6      .1       0
Bank Sta=1738.7,1758.6
XS Rating Curve= 0 ,0
Exp/Cntr=0.3,0.1

Type RM Length L Ch R = 1 ,9733.5  ,521.2,500.6,479.4
XS GIS Cut Line= 2
     1723117.021      352678.971     1723533.359      351980.746
#Sta/Elev= 30
       0   885.2    19.9  880.83    55.8  868.08    79.7  856.31   103.6  841.57
   139.5  827.67   215.2  825.48   294.9  820.84   338.7  820.15   354.7  814.88
   374.6  813.77   378.6  811.65   382.6  808.03   386.5  805.93   394.5  805.39
   406.5  807.31   430.4  811.88   470.2  811.42   490.2  812.45   498.1  815.18
   510.1  823.46     526  829.22   545.9  833.61   557.9  838.76   589.8   845.4
   657.5  861.69   741.2  884.96   757.1  890.22   773.1  893.77   812.9  906.17
#Mann= 3 , 0 , 0
       0     .08       0   382.6    .045       0   406.5     .08       0
Bank Sta=382.6,406.5
XS Rating Curve= 0 ,0
Exp/Cntr=0.3,0.1