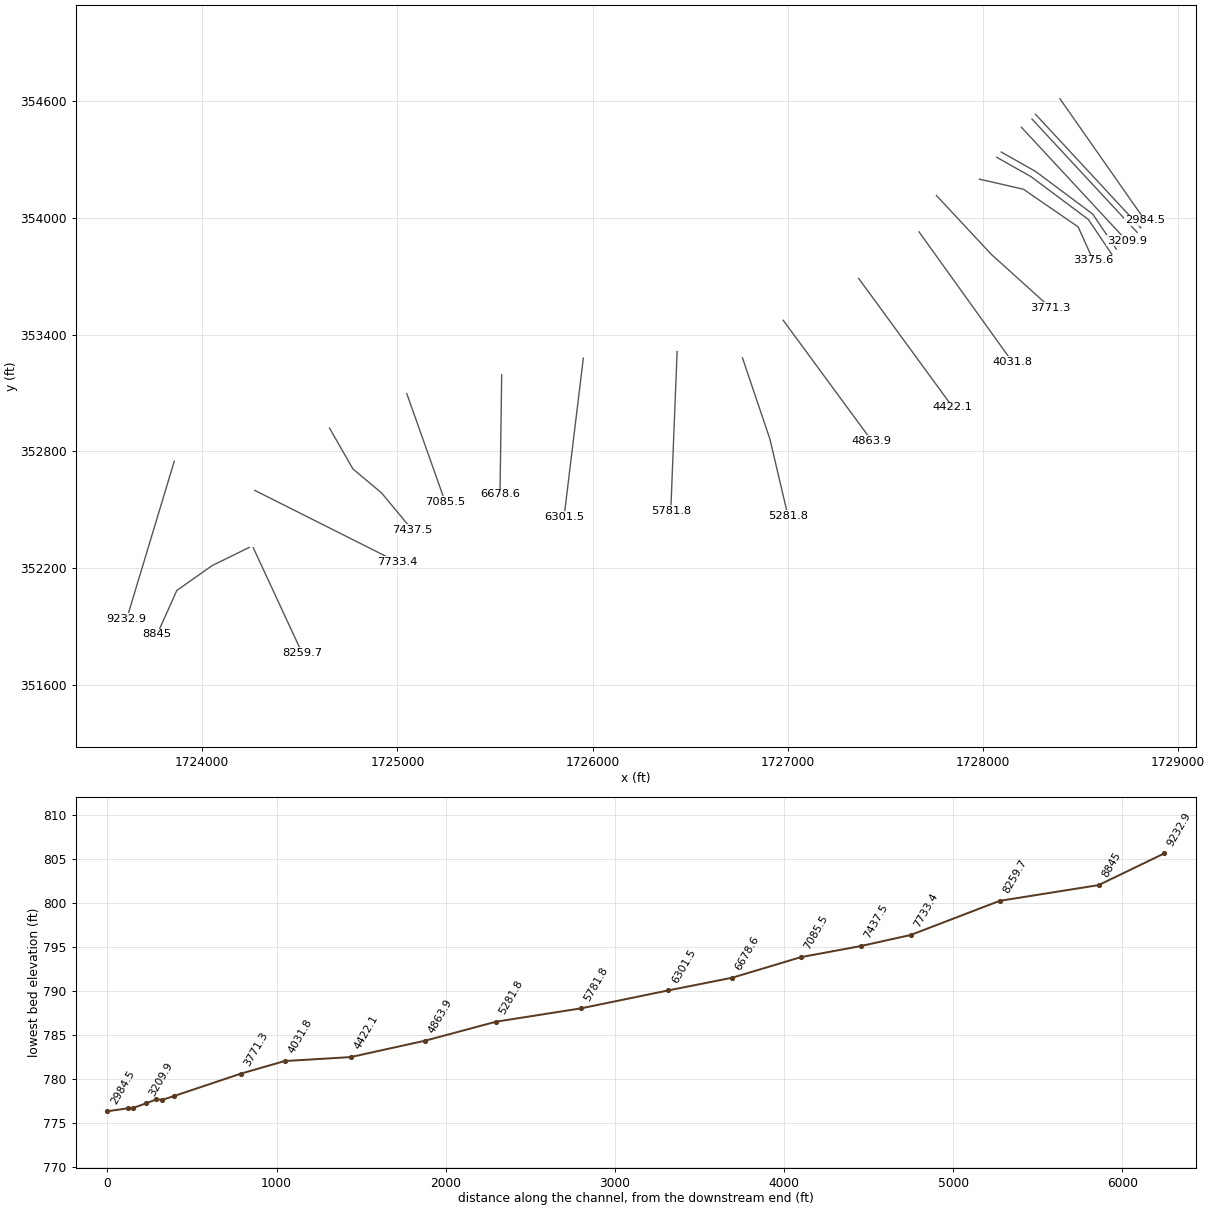
HEC-RAS study HEWETTCK.prj: HEWETTCK

--- HEWETTCK.g01 (geometry) --- (continued)

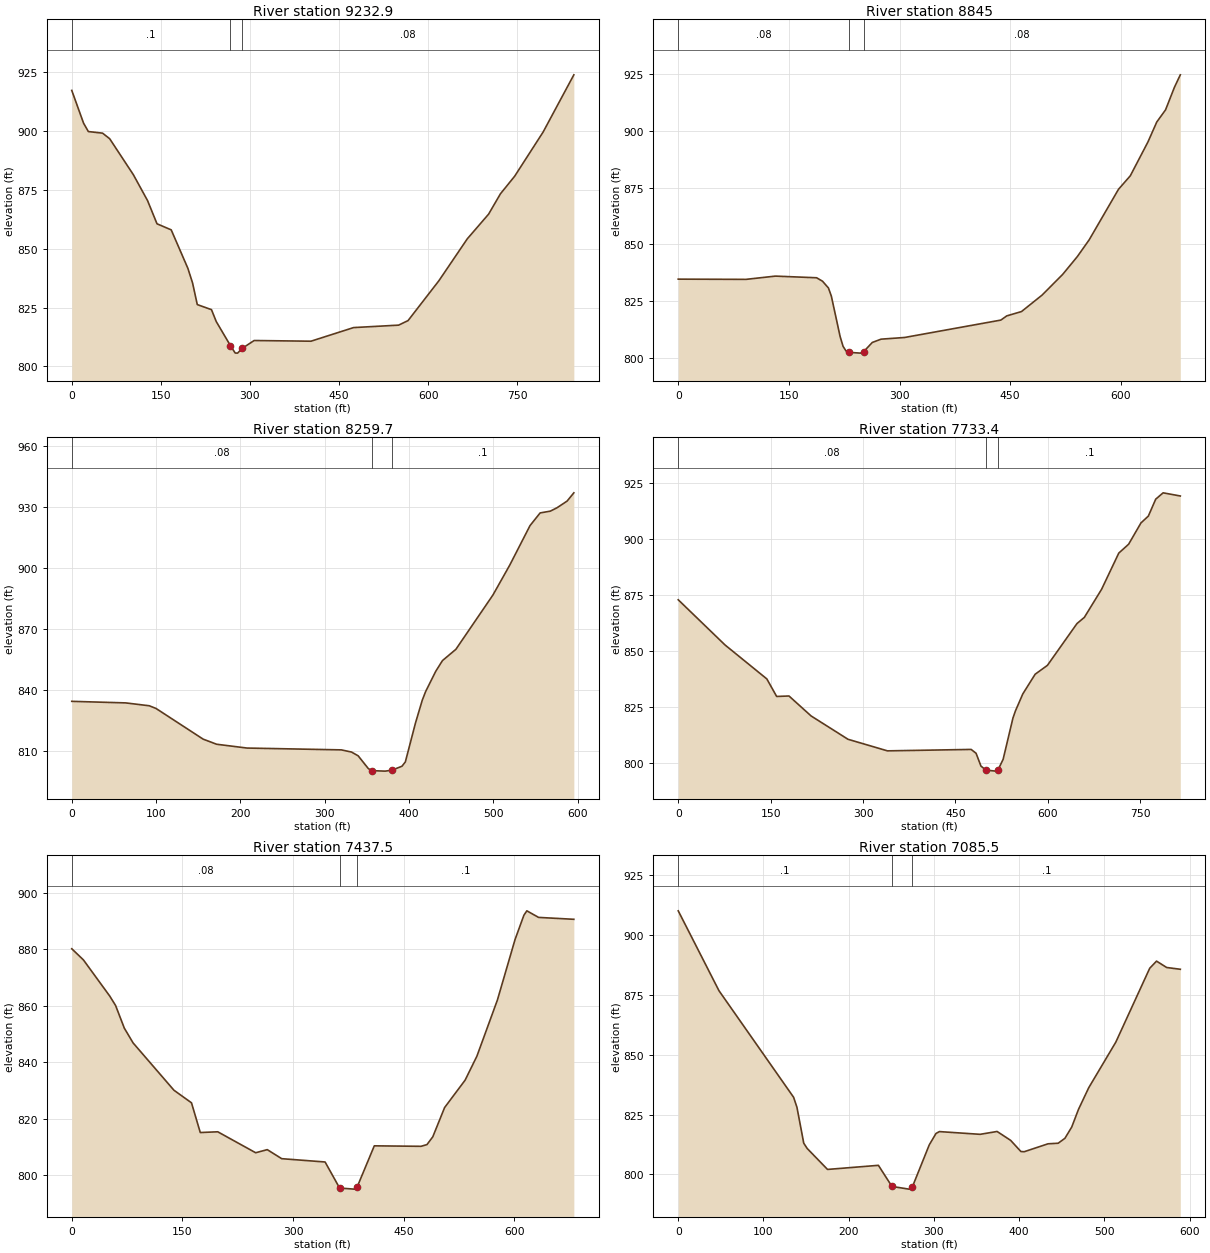
Type RM Length L Ch R = 1 ,9232.9  ,404.6,387.9,371.4
XS GIS Cut Line= 2
     1723856.276      352748.975     1723612.798      351939.585
#Sta/Elev= 30
       0  917.35    19.9  903.41    27.9  899.86    51.8  899.18    63.8  896.82
   103.7  881.51   127.6  870.49   143.5  860.64   167.4  858.06   195.4  841.74
   203.3  835.54   211.3  826.29   235.2  824.13   243.2  819.08   267.1  808.84
   275.1  805.69   279.1  805.65   287.1  807.71     307  811.01   402.7  810.72
   474.4  816.51   550.2  817.55   566.1  819.48     618  836.42   665.8  854.24
   701.7  864.74   721.6  873.38   745.6  880.88   793.4  899.62   845.2  923.98
#Mann= 3 , 0 , 0
       0      .1       0   267.1    .045       0   287.1     .08       0
Bank Sta=267.1,287.1
XS Rating Curve= 0 ,0
Exp/Cntr=0.3,0.1

Type RM Length L Ch R = 1 ,8845    ,550.2,585.3,620
XS GIS Cut Line= 4
     1724240.496      352306.826     1724050.609       352213.51
     1723869.402      352085.472     1723768.491      351859.777
#Sta/Elev= 30
       0  834.67    91.8  834.57   131.7  836.01   187.6  835.28   195.6  833.76
   203.6   830.8   207.6  827.18   219.5  809.33   223.5  805.03   227.4  803.04
   231.4  802.39   247.2  802.05   251.2  802.64   263.1  806.75     275  808.21
   306.7  808.94   437.4  816.62   445.4  818.47   465.4  820.38   493.3  827.64
   521.2  836.76   541.1  844.62   557.1  851.98   596.9  874.29   612.9  880.24
   636.8  895.15   648.8  903.97   660.7  909.32   672.7  919.24   680.7  924.76
#Mann= 3 , 0 , 0
       0     .08       0   231.4    .045       0   251.2     .08       0
Bank Sta=231.4,251.2
XS Rating Curve= 0 ,0
Exp/Cntr=0.3,0.1

Type RM Length L Ch R = 1 ,8259.7  ,509.4,526.3,543.1
XS GIS Cut Line= 2
     1724261.224      352304.964     1724511.224        351764.6
#Sta/Elev= 30
       0  834.59    63.9  833.82    91.9  832.41    99.9  831.09   155.8  815.99
   171.8  813.48   207.8  811.61   319.7  810.71   331.7  809.65   339.6   807.8
   351.6  801.55   355.6  800.49   371.6  800.26   379.6  800.71   391.6  802.67
   395.6  804.81   407.6  823.93   415.6  835.08   419.6  839.37   431.6  849.34
   439.6  854.63   455.5  860.17   499.5  886.92   519.5  901.67   543.4     921
   555.4  927.26   567.4  928.13   575.4  929.79   587.4  933.09   595.4  937.15
#Mann= 3 , 0 , 0
       0     .08       0   355.6    .045       0   379.6      .1       0
Bank Sta=355.6,379.6
XS Rating Curve= 0 ,0
Exp/Cntr=0.3,0.1

Type RM Length L Ch R = 1 ,7733.4  ,301.8,295.9,290.2
XS GIS Cut Line= 2
     1724268.708      352599.795     1724996.789      352233.041
#Sta/Elev= 30
       0  872.82    75.9  852.68   143.9   837.5   159.8  829.69   179.8   829.9
   215.8  820.98   275.7  810.58   339.7  805.42   475.6  806.06   483.6  804.34
   491.5  798.64   499.5  796.84   515.5  796.38   519.5   797.1   527.5  801.62
   543.5   820.1   547.5  823.24   559.5  830.84   579.5   839.6   599.4  843.56
   647.4   862.2   659.4  864.97   687.4   877.5   715.3  893.64   731.3  897.61
   751.3   907.1   763.3  910.15   775.3  917.71   787.3  920.53   815.2  919.12
#Mann= 3 , 0 , 0
       0     .08       0   499.5    .045       0   519.5      .1       0
Bank Sta=499.5,519.5
XS Rating Curve= 0 ,0
Exp/Cntr=0.3,0.1

Type RM Length L Ch R = 1 ,7437.5  ,365.2,352,338.5
XS GIS Cut Line= 4
     1724651.849      352919.548     1724771.641      352709.912
     1724918.776      352586.214     1725076.328       352396.11
#Sta/Elev= 30
       0  880.23    15.8  876.28    51.5  863.47    59.4  860.14    71.2  852.14
    83.1   846.9   138.5  830.14   162.3  825.68   174.2  815.16   197.9  815.42
   249.3     808     265   809.1   284.6   805.9   343.4  804.73   363.1   795.5
   382.7  795.12   386.6  795.71   410.1  810.45   473.5  810.28   481.5  810.89
   489.4  813.64   505.4     824   533.2   833.7   549.2   842.2     577  862.09
   600.9   883.5   612.9   892.1   616.9  893.66   632.8  891.33   680.6  890.66
#Mann= 3 , 0 , 0
       0     .08       0   363.1    .045       0   386.6      .1       0
Bank Sta=363.1,386.6
XS Rating Curve= 0 ,0
Exp/Cntr=0.3,0.1

Type RM Length L Ch R = 1 ,7085.5  ,415.6,406.8,398.1
XS GIS Cut Line= 2
     1725047.682      353096.631     1725244.185      352541.201
#Sta/Elev= 30
       0  910.01    47.8  876.68   135.4   832.2   139.3  828.05   147.3  813.04
   151.3  810.85   175.2  802.09   234.9   803.8   250.8  794.99   270.7  793.87
   274.7  794.74   294.6  812.35   302.5   817.1   306.5  817.88   354.3  816.74
   374.2  817.93   390.1  814.22   402.1  809.57     406  809.48   433.9  812.78
   445.9  813.03   453.8  815.08   461.8  819.79   469.7  827.14   481.7  836.17
   513.5   855.2   553.3  886.04   561.3  889.02   573.2  886.36   589.2  885.62
#Mann= 3 , 0 , 0
       0      .1       0   250.8    .045       0   274.7      .1       0
Bank Sta=250.8,274.7
XS Rating Curve= 0 ,0
Exp/Cntr=0.3,0.1

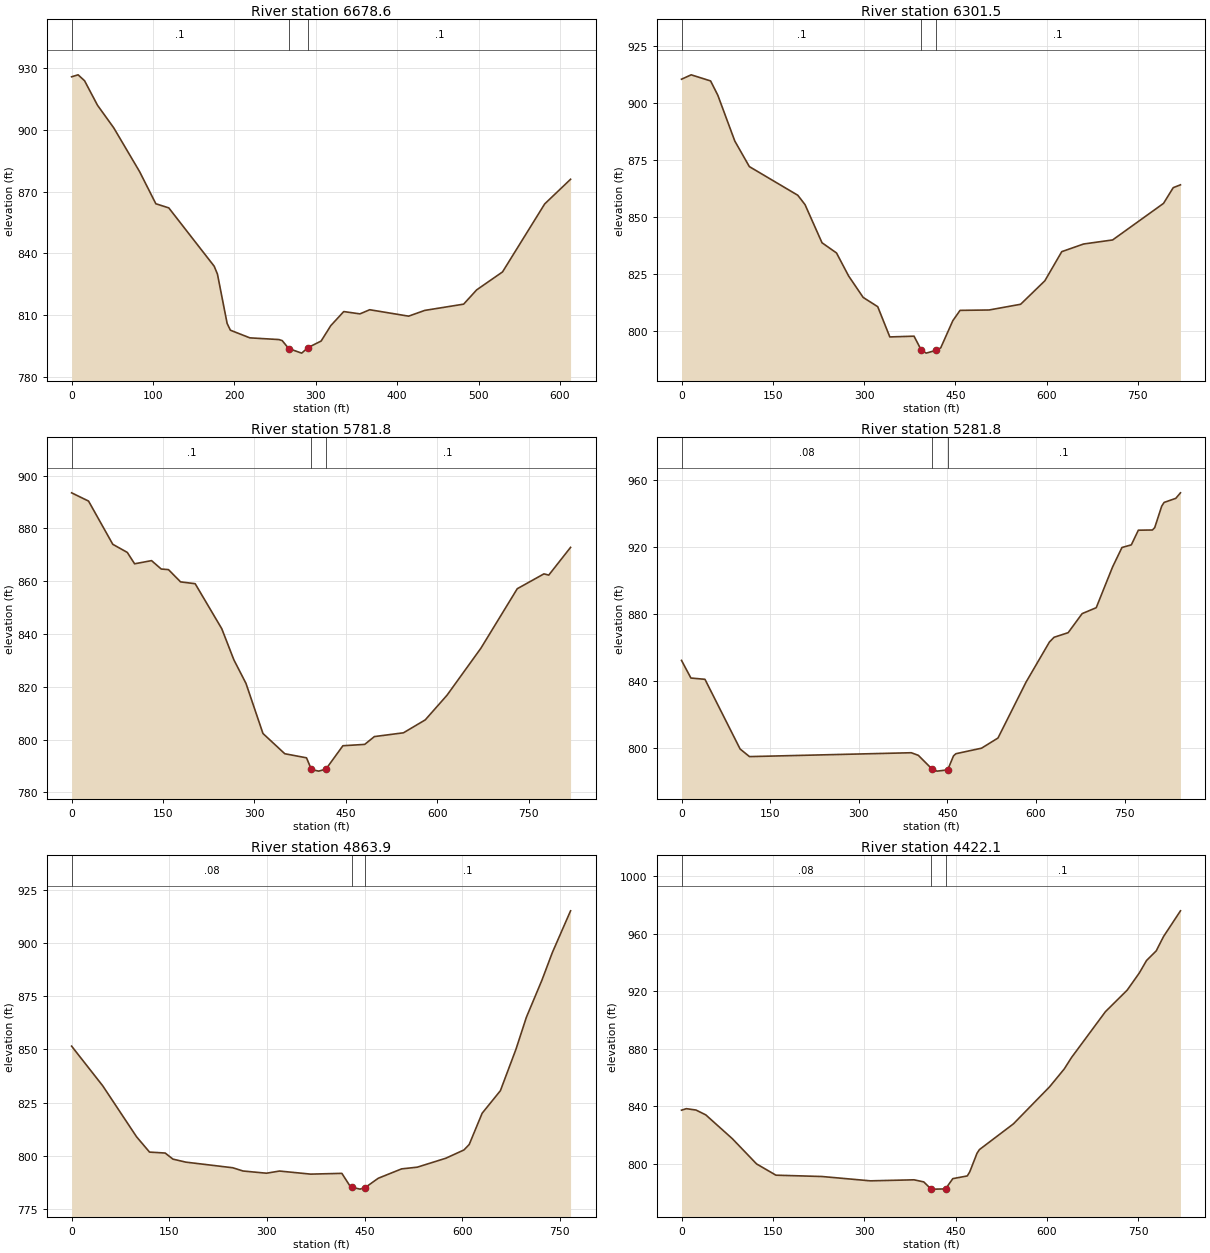
Type RM Length L Ch R = 1 ,6678.6  ,379.8,377.1,374.4
XS GIS Cut Line= 2
     1725533.899      353193.328     1725525.218      352580.263
#Sta/Elev= 30
       0  925.78       8  926.73    15.9  923.86    31.8  911.96    51.8  900.96
    83.6  879.66   103.5   864.1   119.4  862.09   175.2  833.75   179.2  829.93
   191.1  805.96   195.1  802.67     219  798.95   254.8  798.12   258.8   797.6
   266.8  793.75   282.7  791.53   290.6  794.24   306.6   797.4   318.5   804.9
   334.4  811.72   354.3   810.6   366.3  812.61   414.1  809.49     434  812.29
   481.7  815.32   497.7  822.25   529.5  830.98   581.3  864.01   613.1  875.99
#Mann= 3 , 0 , 0
       0      .1       0   266.8    .045       0   290.6      .1       0
Bank Sta=266.8,290.6
XS Rating Curve= 0 ,0
Exp/Cntr=0.3,0.1

Type RM Length L Ch R = 1 ,6301.5  ,517.6,519.7,521.7
XS GIS Cut Line= 2
     1725952.175      353278.777     1725853.612      352464.596
#Sta/Elev= 30
       0  910.34    15.9  912.27    47.8  909.59    59.7  903.29    87.6   883.2
   111.5  871.98   191.1   859.4     203   855.3   230.9  838.55   254.8  834.05
   274.7  823.94   298.6  814.54   322.5  810.48   342.4   797.2   382.2  797.53
   394.1   791.4   402.1  790.09     418  791.29     426  792.38   445.9  804.31
   457.8  808.86   505.6  809.03   557.4  811.54   597.2  821.85     625  834.64
   660.9     838   708.6  839.78   792.3  855.84   808.2  862.73   820.1  863.98
#Mann= 3 , 0 , 0
       0      .1       0   394.1    .045       0     418      .1       0
Bank Sta=394.1,418
XS Rating Curve= 0 ,0
Exp/Cntr=0.3,0.1

Type RM Length L Ch R = 1 ,5781.8  ,490.8,500,506.8
XS GIS Cut Line= 3
     1726432.601      353312.552     1726416.364      352903.375
     1726400.127      352494.197
#Sta/Elev= 30
       0  893.49    27.8  890.36    67.6  873.98    91.4  870.91   103.4   866.6
   131.2   867.8   147.1  864.62     159  864.39   178.9  859.74   202.8  859.06
   246.5  841.99   266.4  830.18   286.2  821.29   314.1   802.3   349.9  794.63
   385.6  793.08   393.6  788.66   405.5  788.04   417.4  788.78   445.3  797.66
   481.1  798.17     497  801.13   544.7  802.56   580.5  807.46   616.2   816.8
   671.9  834.64   731.5  857.15   775.3  862.78   783.2  862.31     819  872.82
#Mann= 3 , 0 , 0
       0      .1       0   393.6    .045       0   417.4      .1       0
Bank Sta=393.6,417.4
XS Rating Curve= 0 ,0
Exp/Cntr=0.3,0.1

Type RM Length L Ch R = 1 ,5281.8  ,410.1,417.9,428.1
XS GIS Cut Line= 3
      1726767.36      353280.622     1726908.032      352863.085
     1727000.369      352469.766
#Sta/Elev= 30
       0  852.41    15.9  841.93    39.7  841.17    99.2  799.69   115.1  795.17
     389  797.47   400.9  795.92   424.7  787.56   432.7  786.53   450.6  787.28
   460.4  795.59   464.4  796.88   507.9  800.19   535.7  806.23   583.2   839.5
   622.8  863.37   630.7  866.19   654.5  868.92   678.2  880.27     702  883.77
   729.7  908.04   745.6  919.62   761.4  921.17   773.3   929.9   797.1  930.02
     801  931.42   812.9  944.26   816.9  946.42   836.7  948.86   844.6  952.14
#Mann= 3 , 0 , 0
       0     .08       0   424.7    .045       0   450.6      .1       0
Bank Sta=424.7,450.6
XS Rating Curve= 0 ,0
Exp/Cntr=0.3,0.1

Type RM Length L Ch R = 1 ,4863.9  ,441.8,441.8,441.6
XS GIS Cut Line= 2
      1726976.08      353473.439     1727429.205      352855.384
#Sta/Elev= 30
       0  851.49    47.9  832.83    99.8  808.93   119.7  801.76   143.7  801.32
   155.7  798.45   175.6  797.04   247.5  794.41   263.4  792.88   299.4  791.85
   319.3  792.87   367.2  791.42   415.1  791.78   427.1  786.09   431.1  785.21
     443  784.38     451  785.12     471  789.48   506.9  793.88   530.9  794.68
   574.8  798.88   602.7  802.78   610.7  805.32   630.6     820   658.6  830.57
   682.5     850   698.5  865.01   722.5  882.52   738.4   895.4   766.4     915
#Mann= 3 , 0 , 0
       0     .08       0   431.1    .045       0     451      .1       0
Bank Sta=431.1,451
XS Rating Curve= 0 ,0
Exp/Cntr=0.3,0.1

Type RM Length L Ch R = 1 ,4422.1  ,390.5,390.3,390
XS GIS Cut Line= 3
     1727362.644      353688.574     1727603.785      353357.603
     1727844.975      353026.669
#Sta/Elev= 30
       0  837.33       8  838.37    23.8  837.42    39.8  834.08    83.5   817.5
   123.2  800.01     155  792.19   230.6  791.27   310.1  788.26   381.7  788.98
   397.6  787.53   409.5  782.64   417.4  782.51   433.4  782.68   445.3  789.79
   469.1  791.67   473.1  794.49     485  807.37     489  809.95   544.7  827.79
   604.3  853.62   628.2  865.93   640.1  873.85   695.8  905.71   731.5  920.67
   751.4  932.57   763.3  941.25   779.2  947.95   791.2   957.9     819  975.75
#Mann= 3 , 0 , 0
       0     .08       0   409.5    .045       0   433.4      .1       0
Bank Sta=409.5,433.4
XS Rating Curve= 0 ,0
Exp/Cntr=0.3,0.1

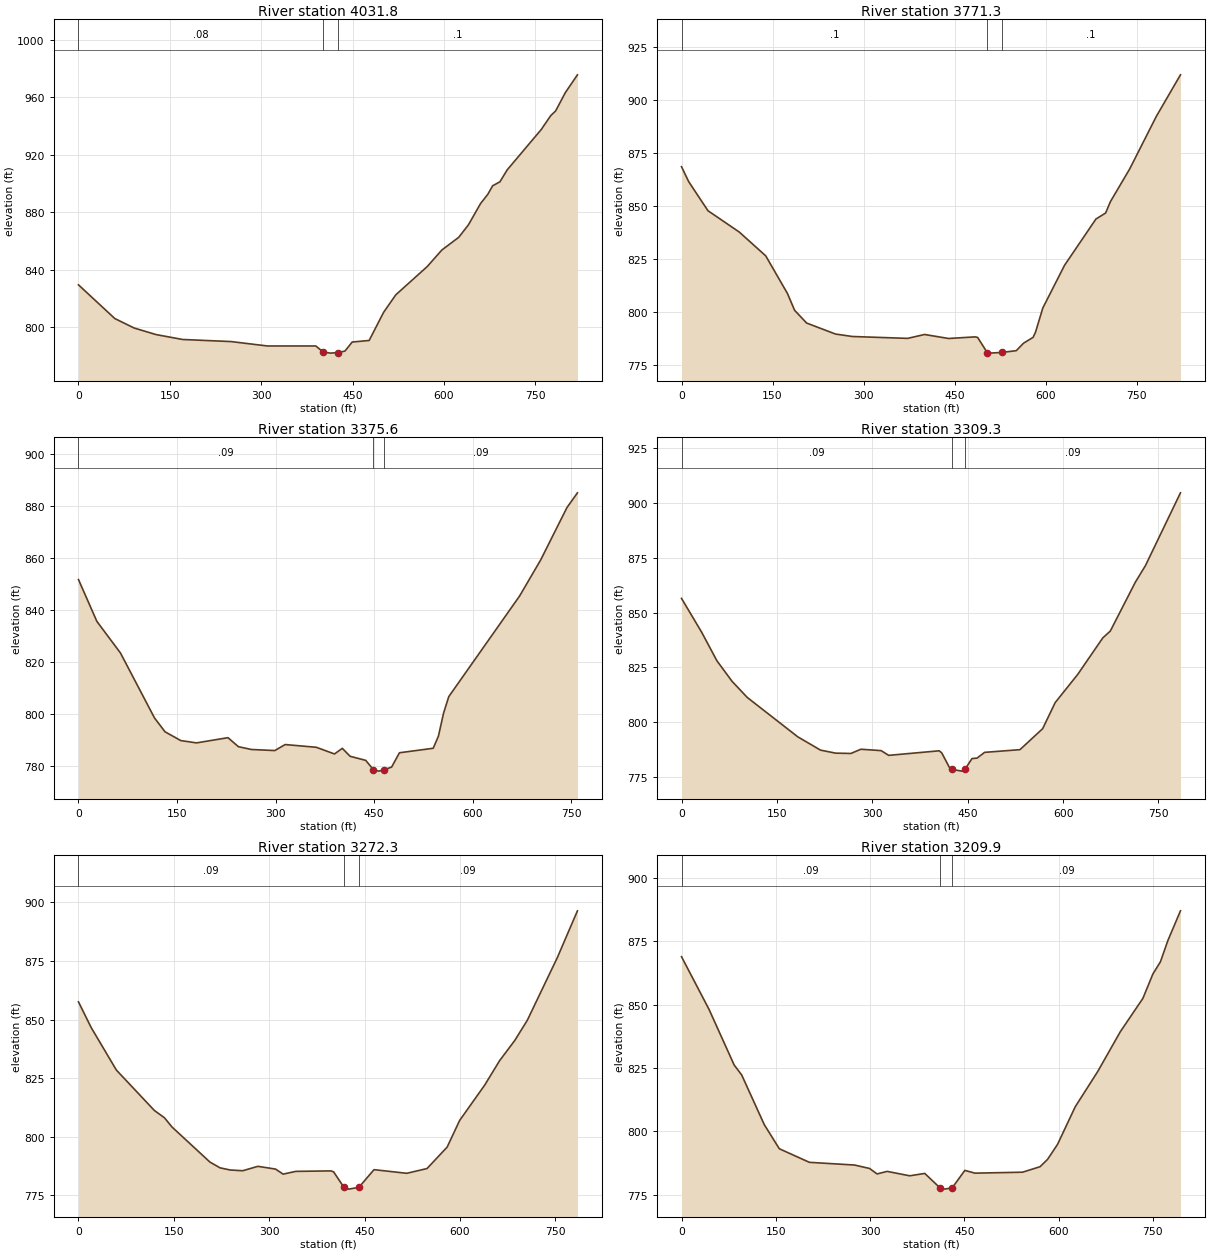
Type RM Length L Ch R = 1 ,4031.8  ,255,260.5,266
XS GIS Cut Line= 3
     1727671.989      353927.608     1727910.277      353594.578
     1728148.565      353261.548
#Sta/Elev= 30
       0  829.58    59.6  806.13    91.4  799.53   127.2  794.98     171  791.55
   250.5   790.1   310.1  787.04   389.6  787.04   401.6  782.84   413.5  782.06
   425.4  782.45   437.3  783.46   449.3  789.79   477.1  790.86   500.9  810.48
   520.8  822.61   572.5  842.32   596.4   853.8   624.2  862.67   640.1  871.34
     660  886.16   671.9  892.58   679.8   898.5   691.8  901.29   703.7  909.59
   759.4  937.56   775.3  947.41   783.2  950.56   799.1  963.32     819  975.72
#Mann= 3 , 0 , 0
       0     .08       0   401.6    .045       0   425.4      .1       0
Bank Sta=401.6,425.4
XS Rating Curve= 0 ,0
Exp/Cntr=0.3,0.1

Type RM Length L Ch R = 1 ,3771.3  ,392.9,395.7,398.4
XS GIS Cut Line= 3
     1727761.093       354114.35     1728041.912       353812.37
     1728345.883      353537.337
#Sta/Elev= 30
       0  868.49    11.9  861.41    43.6  847.74    95.2  837.69   138.8  826.47
   174.5  808.78   186.4   800.8   206.2   794.8   253.8  789.61   281.5  788.46
   372.7  787.57   400.5  789.41   440.2  787.52     484  788.28     488  788.03
   503.9  780.86   507.9  780.62   527.8  780.94   551.7  781.78   563.6  785.28
   579.5  788.08   583.5  790.57   595.4  801.86   631.3  822.04     683  843.83
   698.9  846.64   706.9  852.04   738.7  867.47   782.5   892.2   822.3  911.79
#Mann= 3 , 0 , 0
       0      .1       0   503.9    .045       0   527.8      .1       0
Bank Sta=503.9,527.8
XS Rating Curve= 0 ,0
Exp/Cntr=0.3,0.1

Type RM Length L Ch R = 1 ,3375.6  ,67.3,66.3,65.3
XS GIS Cut Line= 4
     1727981.532      354198.329     1728207.227      354146.246
     1728487.175      353953.103     1728564.215      353781.662
#Sta/Elev= 30
       0  851.82      28  835.72    63.9  823.56   115.8  798.52   131.8  793.21
   155.8  789.83   179.7  788.94   227.6  790.95   243.5  787.48   263.3   786.4
   298.9  785.99   314.7   788.3   362.1  787.25   389.8  784.68   401.7  786.84
   413.6  783.78   437.3  782.22   449.1  778.62     457  778.07     465  778.53
   476.8  779.64   488.7  785.14   540.1  786.87     548   791.5   555.9  800.42
   563.8  806.75   671.7  845.52   703.7  859.35   743.7  879.52   759.7  885.21
#Mann= 3 , 0 , 0
       0     .09       0   449.1    .045       0     465     .09       0
Bank Sta=449.1,465
XS Rating Curve= 0 ,0
Exp/Cntr=0.3,0.1

Type RM Length L Ch R = 1 ,3309.3  ,36.9,36.9,36.6
XS GIS Cut Line= 4
      1728070.27      354310.428     1728246.659      354210.428
      1728539.02      353991.678     1728659.854      353811.817
#Sta/Elev= 30
       0  856.44    31.8  840.96    55.7  827.97    79.5  818.62   103.4  811.26
   182.9  793.29   218.6  787.24   242.4  785.86   266.3  785.72   282.1  787.65
   313.9  787.01   325.8  784.85   405.2  786.93   409.2  785.99     421  779.48
     425  778.44   440.9  777.66   445.6  778.44   456.8   783.4   464.7  783.59
   476.6  786.22   532.2  787.45   567.9  797.03   587.6  808.92   623.1   821.8
   662.4   838.4   674.3  841.56   713.7  863.87   729.4  871.32   784.6  904.59
#Mann= 3 , 0 , 0
       0     .09       0     425    .045       0   445.6     .09       0
Bank Sta=425,445.6
XS Rating Curve= 0 ,0
Exp/Cntr=0.3,0.1

Type RM Length L Ch R = 1 ,3272.3  ,67.3,62.4,57.8
XS GIS Cut Line= 4
     1728093.187      354337.512     1728269.576      354237.512
     1728561.937      354018.762      1728682.77      353838.901
#Sta/Elev= 30
       0  857.56    19.9  846.63    59.6  828.47   119.3  811.25   135.2  808.13
   147.1  804.18   206.7  789.24   222.6  786.78   238.5  785.86   258.3  785.55
   282.1  787.42   309.9  786.25   321.8   784.1   341.7  785.27   397.2  785.47
   401.2  785.05   417.1  778.59     425   777.7   440.9  778.46   464.7     786
   516.3  784.45   548.1  786.48   579.7  795.62   599.4     807   638.8  822.08
   662.4  832.56   686.1  841.12   705.8  849.72   753.1   876.5   784.6  896.38
#Mann= 3 , 0 , 0
       0     .09       0   417.1    .045       0   440.9     .09       0
Bank Sta=417.1,440.9
XS Rating Curve= 0 ,0
Exp/Cntr=0.3,0.1

Type RM Length L Ch R = 1 ,3209.9  ,73.1,72.7,72.7
XS GIS Cut Line= 2
     1728196.355      354464.769     1728735.635      353882.086
#Sta/Elev= 30
       0     869    43.9  848.14    83.8  826.23    95.8  822.29   131.7   802.7
   155.6  793.18   203.5  787.82   275.3  786.75   299.2   785.4   311.2  783.24
   327.2  784.25   363.1   782.5     387  783.44   410.9  777.84   418.9  777.24
   430.9  777.81   450.8  784.64   466.8  783.55   542.6  783.92   570.5  786.09
   582.5     789   598.4  794.95   626.4  809.72   662.3  823.69   698.2  839.38
   734.1  852.54     750  862.16     762  866.98     774  875.45   793.9   887.1
#Mann= 3 , 0 , 0
       0     .09       0   410.9    .045       0   430.9     .09       0
Bank Sta=410.9,430.9
XS Rating Curve= 0 ,0
Exp/Cntr=0.3,0.1

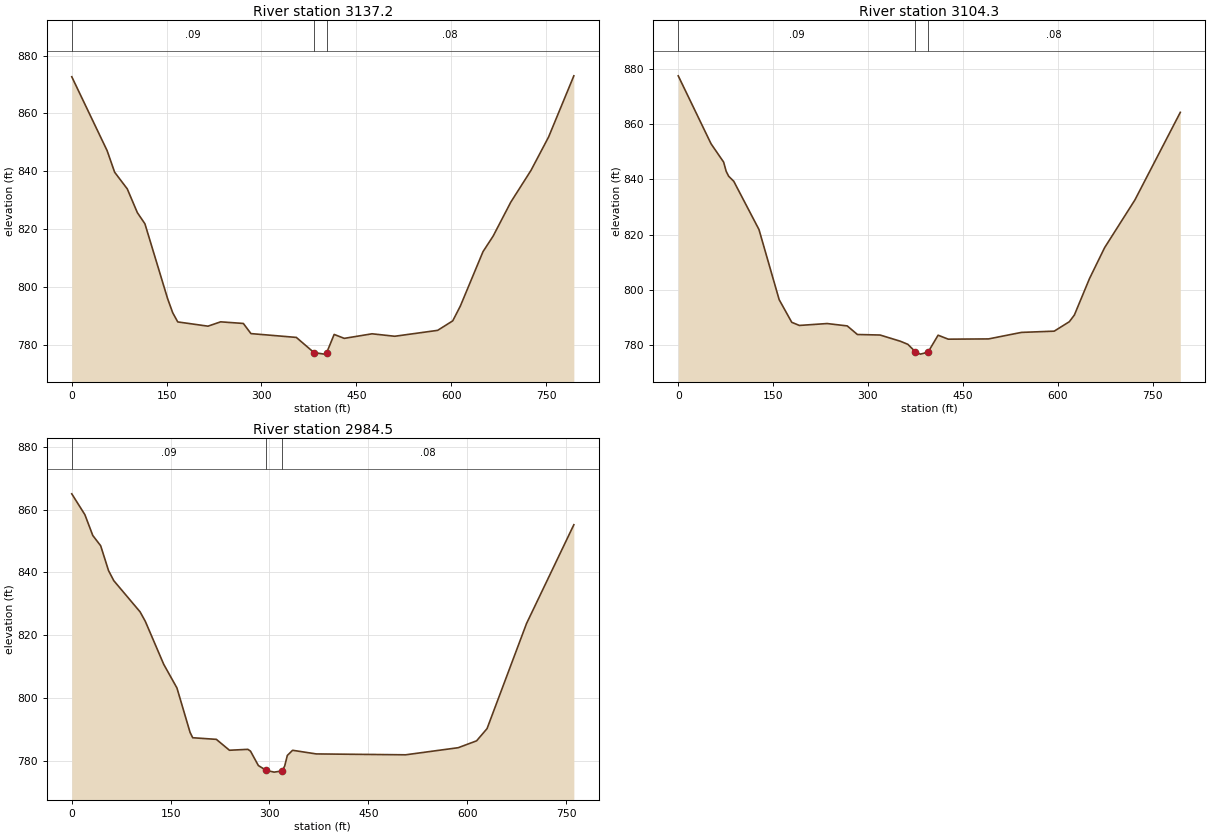
Type RM Length L Ch R = 1 ,3137.2  ,33,32.9,32.4
XS GIS Cut Line= 2
     1728250.609      354507.086     1728789.888      353924.404
#Sta/Elev= 30
       0  872.68    55.9  847.12    67.8  839.66    87.8  833.88   103.7  825.68
   115.7  821.81   151.6   795.9   159.6  791.06   167.6  787.88   215.4  786.41
   235.4  787.91   271.3  787.35   283.3  783.84   355.1  782.52     383  777.28
     399  776.74     403  777.19   414.9  783.55   430.9  782.19   474.8  783.77
   510.7  782.92   578.5  784.96   602.4  788.25   614.4  793.35   650.3   812.2
   666.3  817.57   694.2  829.31   726.1  840.28     754  851.86   793.9     873
#Mann= 3 , 0 , 0
       0     .09       0     383    .045       0     403     .08       0
Bank Sta=383,403
XS Rating Curve= 0 ,0
Exp/Cntr=0.3,0.1

Type RM Length L Ch R = 1 ,3104.3  ,125.7,119.8,113.7
XS GIS Cut Line= 2
     1728269.055      354530.958     1728808.335      353948.276
#Sta/Elev= 30
       0  877.52    51.9   852.9    71.8  846.26    75.8  842.93    79.8  841.12
    87.8  839.32   127.7  821.82   159.6  796.42   179.5  788.22   191.5  787.08
   235.4  787.77   267.3  786.91   283.3   783.8   319.2  783.61   351.1  781.37
   363.1  780.24     375  777.53     383  776.69     395   777.4   410.9  783.55
   426.9  782.11   490.7   782.2   542.6  784.56   594.5  785.01   618.4  788.43
   626.4  790.86   650.3  804.06   674.2  815.26   722.1  832.55   793.9  864.29
#Mann= 3 , 0 , 0
       0     .09       0     375    .045       0     395     .08       0
Bank Sta=375,395
XS Rating Curve= 0 ,0
Exp/Cntr=0.3,0.1

Type RM Length L Ch R = 1 ,2984.5  ,335.4,334.5,333.7
XS GIS Cut Line= 2
     1728393.838      354611.253     1728829.812       353986.46
#Sta/Elev= 30
       0  865.04    19.9   858.4    31.9  851.77    43.9  848.48    55.8  840.58
    63.8  837.36   103.7  827.42   111.7  824.37   139.6  810.69   159.6  803.18
   179.5  789.04   183.5  787.32   219.4   786.8   239.3  783.33   267.2  783.62
   271.2  783.06   283.2  778.45   295.2  776.91   307.1  776.36   319.1  776.74
   323.1   778.3   327.1  781.67   335.1  783.32     371  782.16   506.6  781.88
   586.4  784.14   614.3  786.33   630.2  790.23   690.1  823.71   761.9  855.19
#Mann= 3 , 0 , 0
       0     .09       0   295.2    .045       0   319.1     .08       0
Bank Sta=295.2,319.1
XS Rating Curve= 0 ,0
Exp/Cntr=0.3,0.1