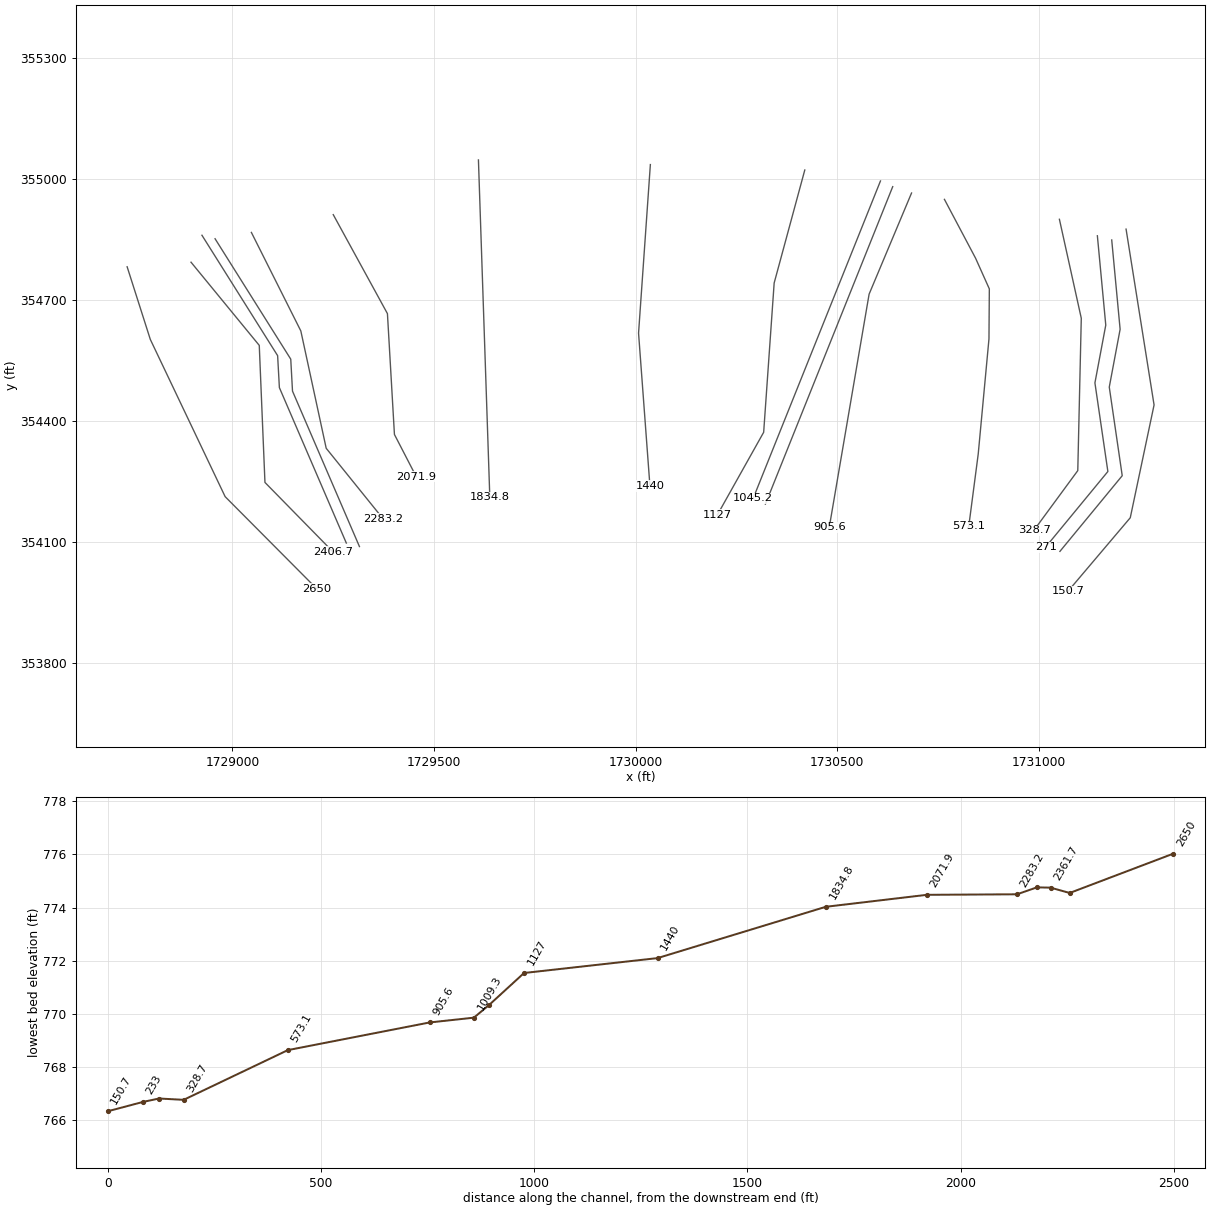
HEC-RAS study HEWETTCK.prj: HEWETTCK

--- HEWETTCK.g01 (geometry) --- (continued)

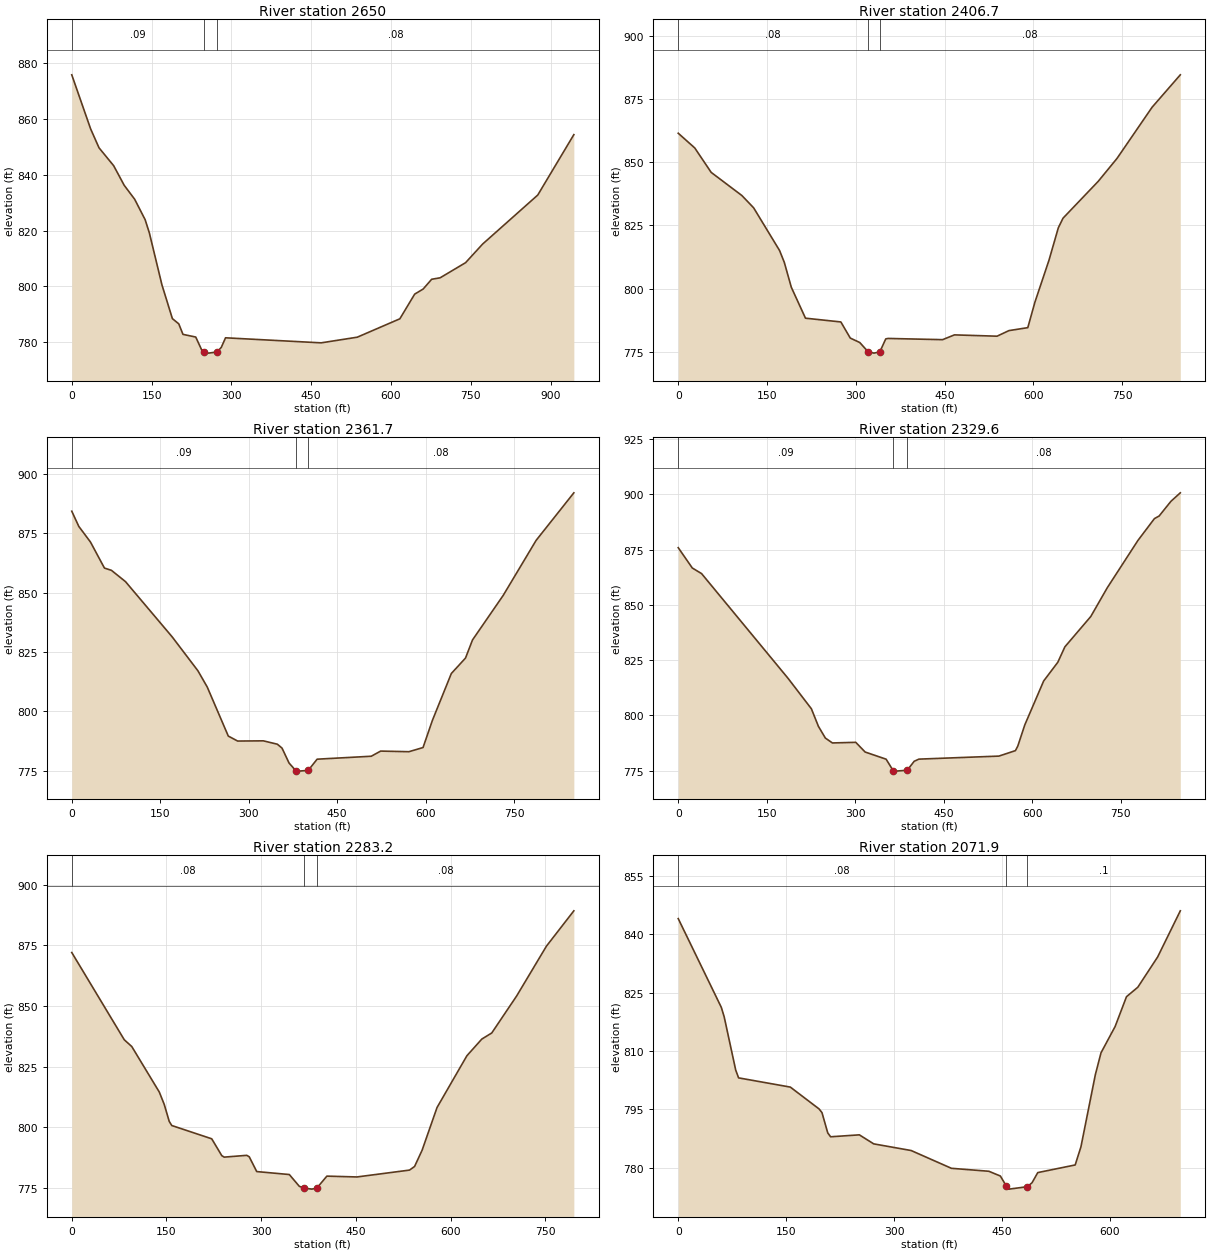
Type RM Length L Ch R = 1 ,2650    ,253.5,243.3,233.1
XS GIS Cut Line= 4
      1728738.89      354781.609     1728796.399      354601.487
     1728981.946      354211.947      1729209.81      353982.998
#Sta/Elev= 30
       0  875.91    35.4  856.53    51.2  849.72    78.8  843.28    98.5  836.27
   118.2  831.26   137.9  823.92   145.8   819.2   169.4  800.58   189.1  788.41
   201.1  786.54     209  782.76     233   781.8     245  776.83     249  776.32
     257  776.03     273  776.44     281  778.09     289  781.53   468.7  779.72
   536.6  781.75   616.6  788.35   644.5  797.21   660.4  799.03   676.4  802.54
   692.3  803.06   740.2   808.5   772.1  815.16   875.8  832.77   943.6  854.44
#Mann= 3 , 0 , 0
       0     .09       0     249    .045       0     273     .08       0
Bank Sta=249,273
XS Rating Curve= 0 ,0
Exp/Cntr=0.3,0.1

Type RM Length L Ch R = 1 ,2406.7  ,44.7,45,45.3
XS GIS Cut Line= 4
     1728897.331      354792.947     1729066.602      354586.784
     1729080.708      354247.157     1729249.978      354074.631
#Sta/Elev= 30
       0  861.45    27.9  855.64    55.7  845.97   107.5  836.84   127.4  831.98
   171.2  815.12   179.2  810.44   191.1  800.57     215  788.36   274.8  786.87
   290.7   780.5   306.7  778.75   320.6  775.17   330.7  774.55   340.6  775.04
   350.7  780.18   354.7  780.35   446.7  779.87   466.7  781.76   538.7  781.24
   558.7  783.44   590.7  784.62   602.7  794.68   626.5  811.27   642.3   824.1
   650.2  827.87   709.7  842.44   741.4  851.48   800.8  871.74   848.4  884.53
#Mann= 3 , 0 , 0
       0     .08       0   320.6    .045       0   340.6     .08       0
Bank Sta=320.6,340.6
XS Rating Curve= 0 ,0
Exp/Cntr=0.3,0.1

Type RM Length L Ch R = 1 ,2361.7  ,32.1,32.1,32.1
XS GIS Cut Line= 4
     1728924.437      354859.734     1729112.154       354561.34
     1729116.494       354482.13      1729282.51       354096.93
#Sta/Elev= 30
       0  884.25    11.9  877.86    31.7  871.26    55.4   860.3    67.3  859.33
    91.1  854.58   170.3  831.29   213.9  817.02   229.7  810.18   265.4  789.52
   281.2  787.42   324.8  787.51   348.6  786.09   356.5  784.45   368.4  778.17
   380.3  774.83   384.3  774.75   400.9  775.05     416  779.78   507.8  781.02
   523.7  783.19   571.7  782.93   595.6  784.69   611.6  796.21   643.6  815.88
   667.6  822.38   679.5  830.02   731.5  848.77   787.4  871.98   851.3  891.99
#Mann= 3 , 0 , 0
       0     .09       0   380.3    .045       0   400.9     .08       0
Bank Sta=380.3,400.9
XS Rating Curve= 0 ,0
Exp/Cntr=0.3,0.1

Type RM Length L Ch R = 1 ,2329.6  ,41.4,46.4,51.8
XS GIS Cut Line= 4
     1728956.989      354851.053     1729144.706      354552.659
     1729149.046      354473.449     1729315.062      354088.249
#Sta/Elev= 30
       0  875.86    23.8  866.68    39.6  864.13   186.2  816.75   225.8  802.96
   237.7  795.02   249.5  789.71   261.4  787.51     301  787.79   316.9   783.4
   352.5  780.16   364.4  774.99   368.4  774.76   388.2  775.15   400.1  779.22
   408.1  780.19   543.7  781.56   571.7  784.03   575.7  786.05   587.6  795.66
   619.6  815.54   643.6  824.02   655.6     831   699.5  844.72   727.5  857.74
   779.4  879.12   807.4  889.01   815.4  890.19   835.3  896.81   851.3  900.68
#Mann= 3 , 0 , 0
       0     .09       0   364.4    .045       0   388.2     .08       0
Bank Sta=364.4,388.2
XS Rating Curve= 0 ,0
Exp/Cntr=0.3,0.1

Type RM Length L Ch R = 1 ,2283.2  ,216.3,211.3,205.8
XS GIS Cut Line= 4
      1729047.07      354866.732     1729169.683      354622.591
     1729232.617      354331.792     1729373.676      354157.096
#Sta/Elev= 30
       0   872.1    83.2   836.1      95  833.34   138.6  814.57   146.5  809.43
   154.4  802.42   158.4  800.74   221.7  795.26   237.6  788.32   241.5   787.7
   277.2  788.44   281.1  787.85     293  781.74   344.6  780.52   360.5  775.64
   368.4  774.92   380.3   774.5   388.2  774.94   404.1  779.86   451.7  779.52
     535  782.35     543  783.84   554.9  790.52   578.6  808.17   625.9  829.52
   649.5  836.39   665.3  838.92   704.7  854.18   751.9  874.73   795.3   889.3
#Mann= 3 , 0 , 0
       0     .08       0   368.4    .045       0   388.2     .08       0
Bank Sta=368.4,388.2
XS Rating Curve= 0 ,0
Exp/Cntr=0.3,0.1

Type RM Length L Ch R = 1 ,2071.9  ,237.8,237.1,236.5
XS GIS Cut Line= 4
     1729250.127      354910.801     1729384.506      354665.506
     1729401.868      354366.027     1729456.135      354261.144
#Sta/Elev= 30
       0     844    59.9  821.18    63.9  818.73    79.9  805.06    83.9  803.07
   155.8   800.7   195.8  795.08   199.8  794.13   207.8  788.93   211.8  787.93
   251.7  788.43   271.7  786.11   323.7   784.4   379.7  779.83   431.7  779.07
   447.7  777.85   455.7  775.36   459.7  774.48   485.1   775.1   491.7  776.11
   499.7  778.73   551.7  780.69   559.7  785.36   579.7  803.88   587.6  809.52
   607.2  816.27     623  823.93   638.7  826.36   666.3  834.14   697.8     846
#Mann= 3 , 0 , 0
       0     .08       0   455.7    .045       0   485.1      .1       0
Bank Sta=455.7,485.1
XS Rating Curve= 0 ,0
Exp/Cntr=0.3,0.1

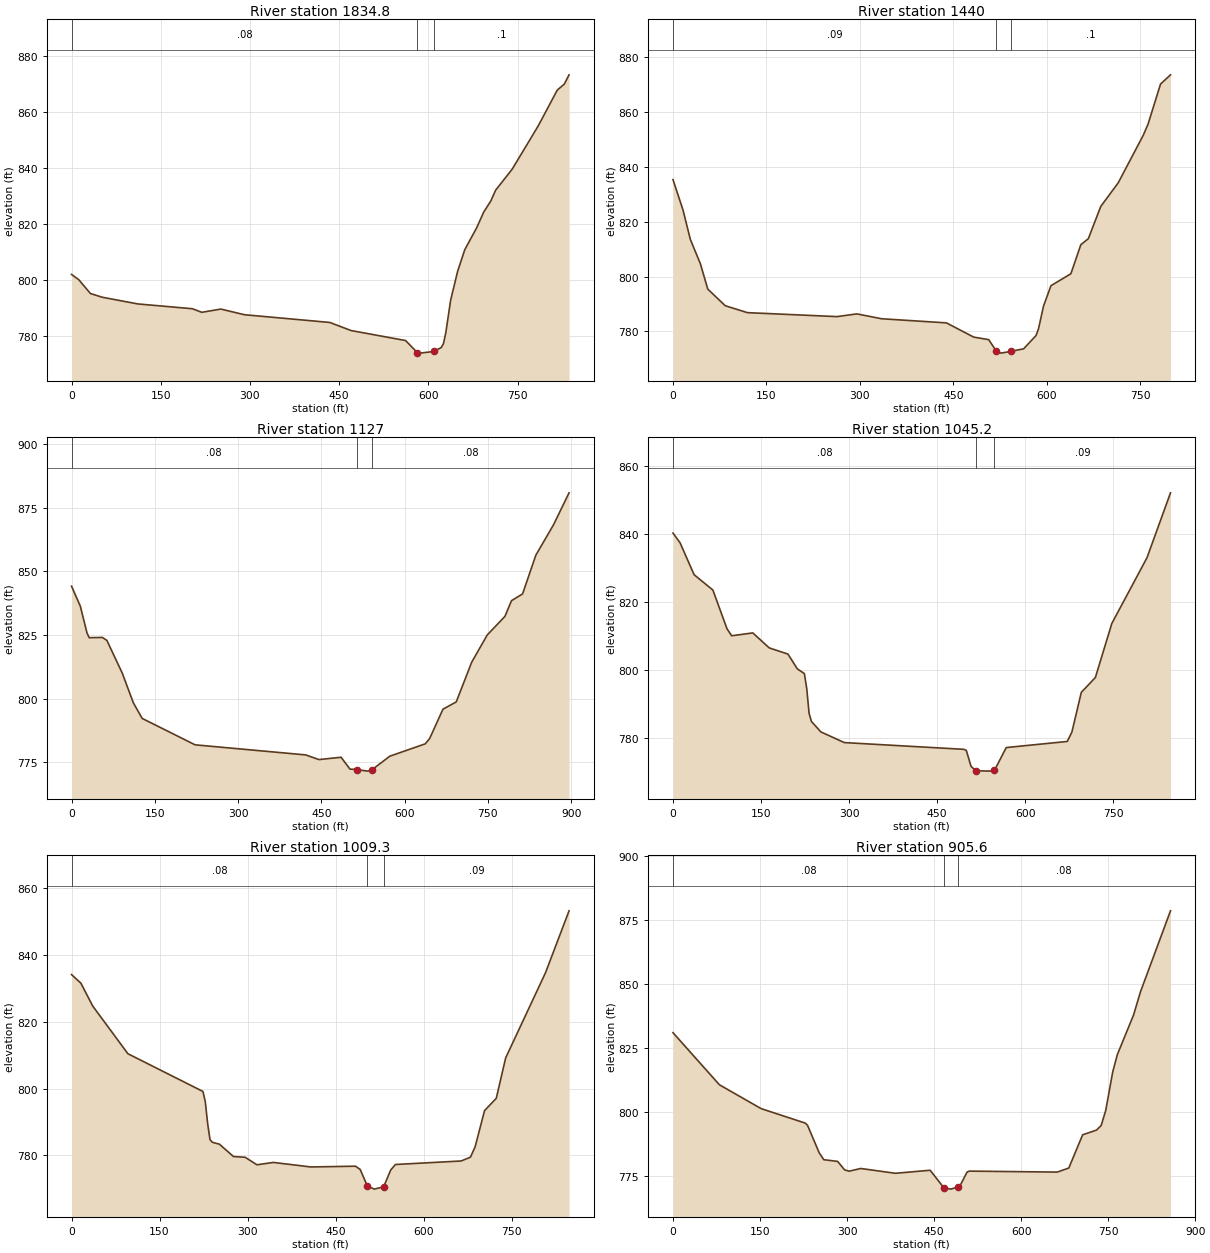
Type RM Length L Ch R = 1 ,1834.8  ,393.9,394.8,395.5
XS GIS Cut Line= 2
     1729610.201      355046.366     1729638.433      354210.265
#Sta/Elev= 30
       0  802.09      12  800.24    31.9  795.27    51.8  793.95   111.5  791.57
   203.2  789.86   219.1  788.58     251  789.74   290.8  787.72   434.2  784.97
   470.1  782.08   561.7  778.52   581.6  774.19   585.6  774.03   609.5  774.62
   621.5     776   625.4   777.4   629.4  781.37   637.4  792.83   649.3  803.25
   661.3  810.94   681.2   818.7   693.2  824.35   705.1  828.31   713.1  832.12
     741  839.63   784.8  855.06   816.7  867.79   828.6  869.96   836.6  873.26
#Mann= 3 , 0 , 0
       0     .08       0   581.6    .045       0   609.5      .1       0
Bank Sta=581.6,609.5
XS Rating Curve= 0 ,0
Exp/Cntr=0.3,0.1

Type RM Length L Ch R = 1 ,1440    ,316.8,313,309.5
XS GIS Cut Line= 3
     1730036.654      355034.917     1730007.357      354617.166
     1730035.569      354238.476
#Sta/Elev= 30
       0  835.29      16   824.3    27.9  813.48    43.9   804.7    55.8  795.44
    83.8  789.37   119.6  786.84   263.2   785.4   295.1  786.39     335  784.62
   438.8  783.12   482.7  777.93   506.7  777.01   518.7  772.92   526.7   772.1
   542.7  772.78   562.7  773.66   582.7  778.51   586.7  781.01   594.7  789.24
   606.6  796.66   638.6  801.01   654.6   811.6   666.6  813.78   686.6  825.54
   714.6  834.14   754.6  851.38   762.5  855.54   782.5  870.11   798.5  873.47
#Mann= 3 , 0 , 0
       0     .09       0   518.7    .045       0   542.7      .1       0
Bank Sta=518.7,542.7
XS Rating Curve= 0 ,0
Exp/Cntr=0.3,0.1

Type RM Length L Ch R = 1 ,1127    ,89.4,81.8,73.7
XS GIS Cut Line= 4
     1730419.663      355021.409     1730343.708      354741.461
     1730317.666      354371.453     1730202.649      354166.374
#Sta/Elev= 30
       0  844.16    15.9  836.28    27.8  825.84    31.8  823.93    55.6  824.04
    63.6  822.89    91.4  810.01   111.3  798.38   127.2  792.24   222.5  781.87
   421.7  777.91   445.6  776.08   485.5  776.98   501.5  772.33   513.4  772.16
   533.4  771.54   541.3   772.1   573.2   777.4   637.1  782.26     645  784.34
     669  795.86   692.9  798.72   720.8  814.33   748.7     825   780.6  832.31
   792.5   838.5   812.4  841.13   836.3  856.35   868.2  868.31   896.1  880.83
#Mann= 3 , 0 , 0
       0     .08       0   513.4    .045       0   541.3     .08       0
Bank Sta=513.4,541.3
XS Rating Curve= 0 ,0
Exp/Cntr=0.3,0.1

Type RM Length L Ch R = 1 ,1045.2  ,36.6,35.9,35.4
XS GIS Cut Line= 2
      1730607.38      354994.282     1730291.625      354207.607
#Sta/Elev= 30
       0  840.24      12   837.4      36  828.01      68   823.5      92  812.14
     100  810.08     136  810.92   163.9  806.53   195.9   804.7   211.9  800.36
   223.9  798.97   227.9   794.6   231.9   787.3   235.9  784.92   251.9  781.86
   291.9  778.72   495.8  776.74   499.8  776.41   507.8  771.76   515.8  770.47
   539.8  770.34   547.8  770.56   567.8  777.26   671.8  779.05   679.7  781.81
   695.7  793.46   719.7  797.83   747.7  813.68   807.7  833.02   847.7  852.05
#Mann= 3 , 0 , 0
       0     .08       0   515.8    .045       0   547.8     .09       0
Bank Sta=515.8,547.8
XS Rating Curve= 0 ,0
Exp/Cntr=0.3,0.1

Type RM Length L Ch R = 1 ,1009.3  ,98.2,103.7,109.1
XS GIS Cut Line= 2
     1730637.762      354980.177     1730322.006      354193.501
#Sta/Elev= 30
       0  834.14      16  831.55      36  824.74      96  810.43   223.9  799.12
   227.9  796.04   231.9  789.51   235.9  784.72   239.9  783.89   251.9  783.33
   275.9  779.63   295.9   779.4   315.9  777.15   343.9  777.86   407.8   776.5
   483.8  776.73   491.8  775.76   503.8  770.88   515.8  769.86   531.8  770.55
   543.8  775.58   551.8  777.24   663.8  778.29   679.7  779.43   687.7  782.56
   703.7  793.38   723.7  797.08   739.7  809.18   807.7  834.74   847.7  853.24
#Mann= 3 , 0 , 0
       0     .08       0   503.8    .045       0   531.8     .09       0
Bank Sta=503.8,531.8
XS Rating Curve= 0 ,0
Exp/Cntr=0.3,0.1

Type RM Length L Ch R = 1 ,905.6   ,330,332.5,334.9
XS GIS Cut Line= 3
      1730684.44      354964.388     1730579.189      354713.737
     1730480.447       354136.48
#Sta/Elev= 30
       0  830.84      80  810.48   151.9  801.15   227.9   795.5   231.9  794.64
   251.9  783.94   259.9  781.18   283.8  780.52   295.8  777.21   303.7  776.69
   323.6  777.75   383.4  775.87   443.2  777.06   467.1  770.15     479  769.68
     491  770.54     495  771.12   506.9  776.36   510.9  776.72   662.3  776.34
   682.2  777.92   706.1  790.92     730  792.76     738  794.54   745.9  800.48
   757.9  815.49   765.9  822.29   793.8  837.74   805.7  846.79   857.5  878.48
#Mann= 3 , 0 , 0
       0     .08       0   467.1    .045       0     491     .08       0
Bank Sta=467.1,491
XS Rating Curve= 0 ,0
Exp/Cntr=0.3,0.1

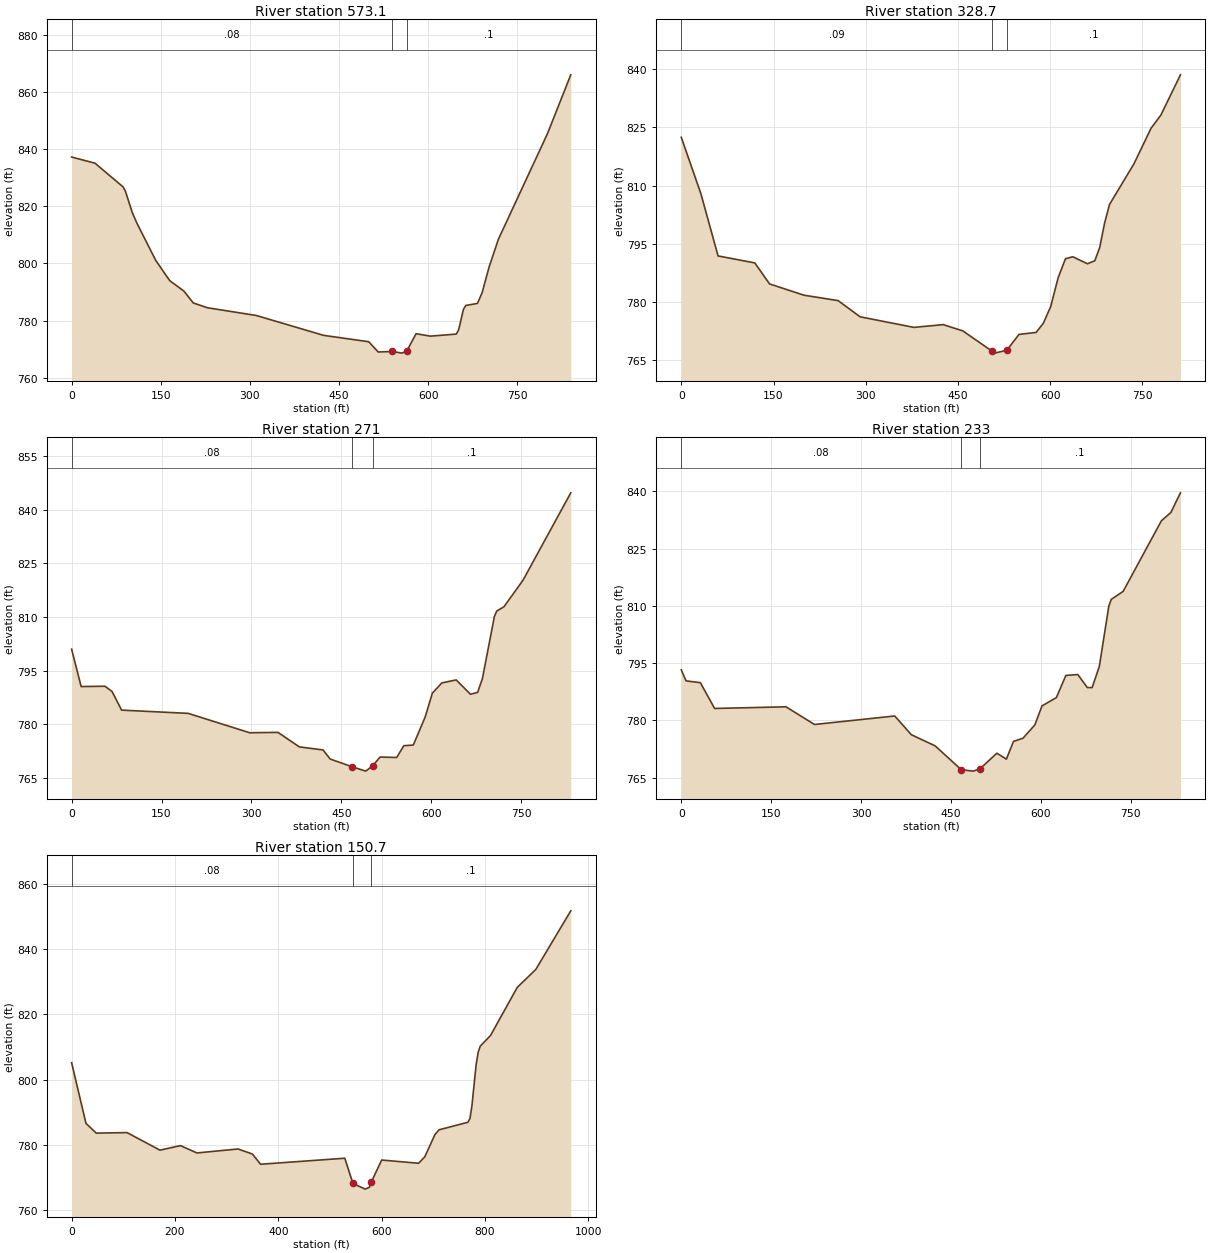
Type RM Length L Ch R = 1 ,573.1   ,242.6,244.4,246.1
XS GIS Cut Line= 6
     1730766.032      354948.656      1730843.29      354802.801
      1730877.39      354726.801     1730876.485      354602.801
     1730849.791      354317.239     1730826.349      354138.243
#Sta/Elev= 30
       0  837.24    39.3  835.09    86.5   826.8    90.4  825.36   102.2  817.71
     110  814.03   141.5  801.09     165     794   188.8  790.36   204.7  786.19
   228.5  784.51   310.4  781.82   424.1  774.85   499.8  772.63   515.8  769.04
   539.7  769.21   555.6  768.64   563.6   769.3   579.5  775.43   603.4  774.58
   647.2   775.3   651.2  776.88   659.2     784   663.1  785.32   682.7  786.03
   690.6  789.81   702.3  798.78     718   808.5   800.4  845.37   839.7     866
#Mann= 3 , 0 , 0
       0     .08       0   539.7    .045       0   563.6      .1       0
Bank Sta=539.7,563.6
XS Rating Curve= 0 ,0
Exp/Cntr=0.3,0.1

Type RM Length L Ch R = 1 ,328.7   ,53.3,57.7,62.1
XS GIS Cut Line= 4
     1731051.194      354899.284     1731105.447      354654.058
     1731096.767      354276.454      1730988.26      354128.884
#Sta/Elev= 30
       0  822.42    31.9  807.87    59.8  791.84   119.6  790.04   143.5  784.63
   199.3  781.72   255.1  780.31   290.9  776.14   378.4  773.41   426.1  774.12
   457.9  772.51   505.6  767.27   509.6  766.77   529.5   767.5   549.3  771.59
   577.2  772.11   589.1  774.51     601  778.82     613   786.2   624.9   791.1
   636.8  791.63   660.7  789.82   672.7   790.6   680.6  793.98   688.6  800.32
   696.6  805.11   736.4  815.61   764.2  824.78   780.2  828.18     812  838.55
#Mann= 3 , 0 , 0
       0     .09       0   505.6    .045       0   529.5      .1       0
Bank Sta=505.6,529.5
XS Rating Curve= 0 ,0
Exp/Cntr=0.3,0.1

Type RM Length L Ch R = 1 ,271     ,36.7,38,41.8
XS GIS Cut Line= 5
     1731145.357      354858.432      1731166.19      354637.078
     1731139.281      354493.848     1731171.399       354274.23
     1731016.885       354086.73
#Sta/Elev= 30
       0  800.99    15.9  790.51    55.6   790.6    67.5  789.13    83.4  783.91
   194.5     783   297.2  777.57   344.4  777.67     380  773.61   419.6  772.75
   431.5  770.21   467.2  768.09   490.9  766.82   502.8  768.38   514.7  770.76
   542.5  770.65   554.4  773.94   570.2  774.13     590  781.97     602  788.66
   617.9  791.54   641.8  792.37   665.7  788.35   677.6  788.88   685.6  792.78
   705.5  810.13   709.5  811.67   721.5  812.86   753.3   820.3     833  844.78
#Mann= 3 , 0 , 0
       0     .08       0   467.2    .045       0   502.8      .1       0
Bank Sta=467.2,502.8
XS Rating Curve= 0 ,0
Exp/Cntr=0.3,0.1

Type RM Length L Ch R = 1 ,233     ,92.6,82.3,69.5
XS GIS Cut Line= 5
     1731180.947      354848.015     1731201.781      354626.661
     1731174.871      354483.432     1731206.989      354263.814
     1731052.475      354076.314
#Sta/Elev= 30
       0  793.21     7.9  790.35    31.8  789.86    55.6  783.11   174.7  783.54
   222.3  778.91   356.2  781.14   383.9  776.23   423.6  773.31   467.2  767.07
     487  766.69   498.1  767.25   526.6  771.38   542.5  769.84   554.4  774.48
   570.2  775.31     590  778.79     602  783.79   625.9  785.95   641.8  791.76
   661.7     792   677.6  788.58   685.6  788.58   697.6  794.11   713.5  809.93
   717.5  811.69   737.4  813.79   801.1  832.26     817  834.46     833  839.61
#Mann= 3 , 0 , 0
       0     .08       0   467.2    .045       0   498.1      .1       0
Bank Sta=467.2,498.1
XS Rating Curve= 0 ,0
Exp/Cntr=0.3,0.1

Type RM Length L Ch R = 1 ,150.7   ,145.9,150.7,155.5
XS GIS Cut Line= 4
     1731216.538      354874.925     1731285.982      354439.161
     1731226.954      354159.647      1731072.44      353977.355
#Sta/Elev= 30
       0  805.15    27.8  786.53    47.7  783.54   107.3   783.7   170.9  778.31
   210.7   779.7   242.5  777.45     322  778.67   349.8  777.12   365.7  773.98
   528.6  775.83   544.4  768.07   568.2  766.34   576.2  766.93   580.1  768.59
     600  775.28   671.4  774.28   683.3  776.24   703.1  783.13   711.1  784.56
   766.8  786.87   770.8  788.02   774.7  792.04   782.7   804.5   786.7  808.39
   790.7  810.24   810.6  813.52   862.4  828.31   898.2   833.8   965.9  851.81
#Mann= 3 , 0 , 0
       0     .08       0   544.4    .045       0   580.1      .1       0
Bank Sta=544.4,580.1
XS Rating Curve= 0 ,0
Exp/Cntr=0.3,0.1

Chan Stop Cuts=-1
Use User Specified Reach Order=0
Composite Channel Slope=5